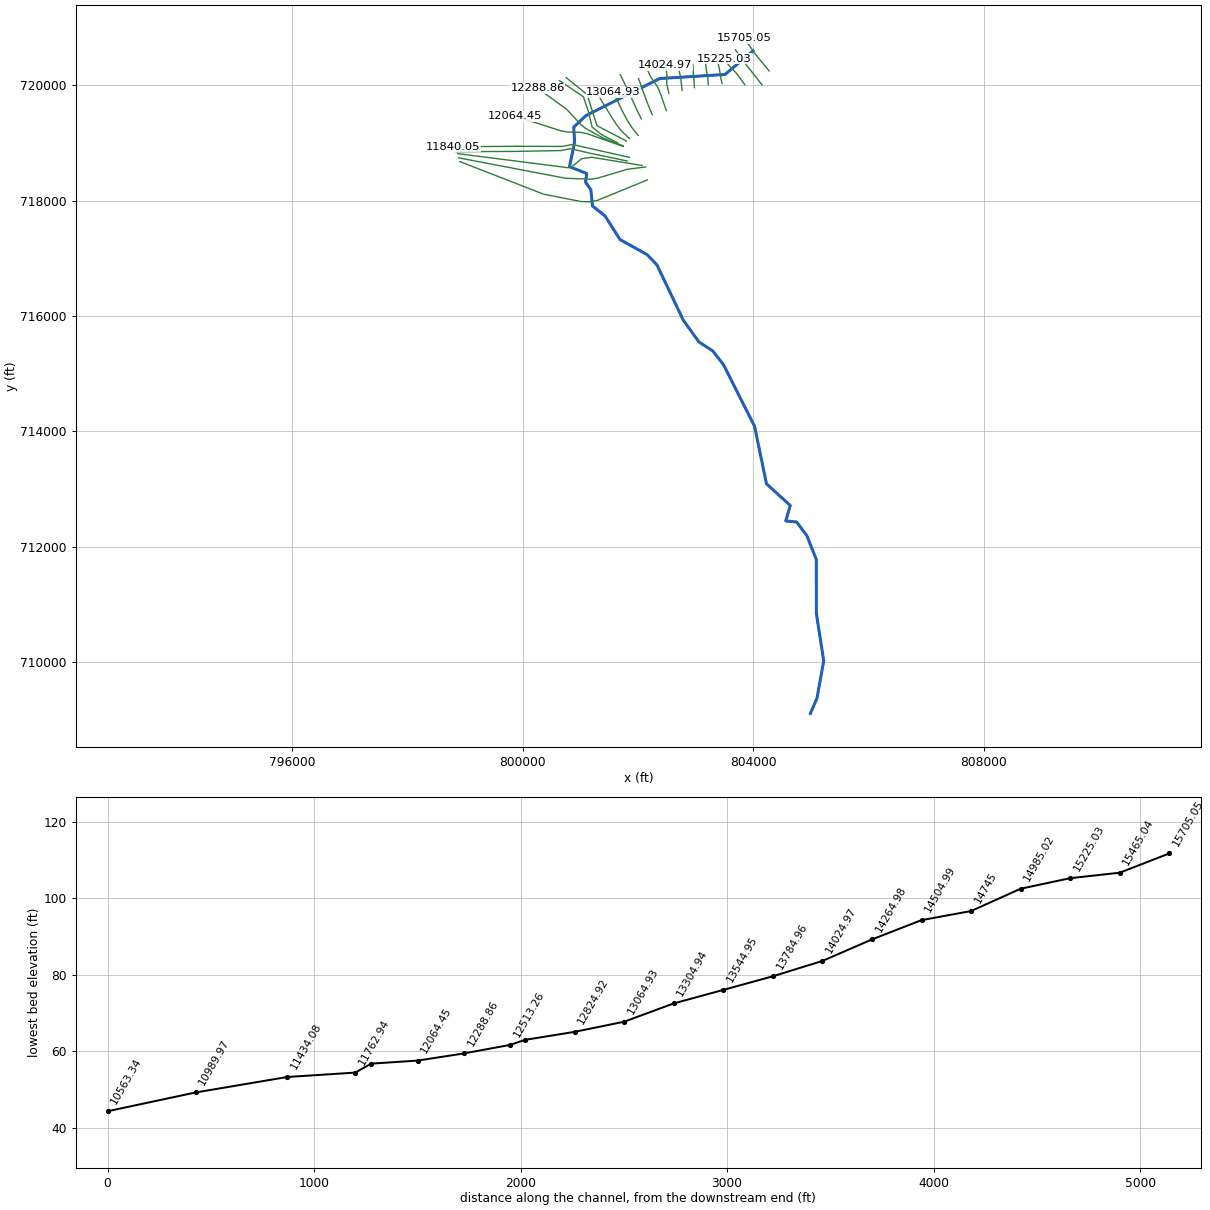
--- 6888_ras.prj (project) ---

Proj Title=6888
Current Plan=p01
Default Exp/Contr=0.3,0.1
English Units
Geom File=g01
Flow File=f01
Plan File=p01
Y Axis Title=Elevation
X Axis Title(PF)=Main Channel Distance
X Axis Title(XS)=Station
BEGIN DESCRIPTION:
RFD model 6888 exported to HEC-RAS
END DESCRIPTION:

--- 6888_ras.p01 (plan) ---

Plan Title=Plan 01
Program Version=4.10
Short Identifier=Plan 01
Geom File=g01
Flow File=f01
Subcritical Flow
Calc Critical at every XS
Secant Critical Depth

--- 6888_ras.f01 (steady flow) ---

Flow Title=Flow 01
Program Version=5.01
Number of Profiles= 6
Profile Names=10yr,25yr,50yr,100yr,100plus,500yr
River Rch & RM=6888,39,15705.05
  751.85 1307.87  1867.1 2425.13  3540.7  5407.1
River Rch & RM=6888,39,15465.04
  754.61 1312.86  1874.4 2434.82 3554.83 5426.62
River Rch & RM=6888,39,15225.03
     757 1317.17 1880.72  2443.2 3567.07 5443.52
River Rch & RM=6888,39,14985.02
  761.78 1325.81 1893.36 2459.96 3591.55 5477.25
River Rch & RM=6888,39,   14745
  767.45 1336.07 1908.38  2479.9 3620.65 5517.36
River Rch & RM=6888,39,14504.99
  769.65 1340.04 1914.19 2487.61 3631.91 5532.86
River Rch & RM=6888,39,14264.98
  777.69 1354.57 1935.47 2515.84 3673.12 5589.53
River Rch & RM=6888,39,14024.97
  782.93 1364.08 1949.41 2534.35 3700.15 5626.76
River Rch & RM=6888,39,13544.95
  793.93  1384.1 1978.86 2573.58 3757.42 5706.03
River Rch & RM=6888,39,13304.94
  795.33 1386.67 1982.64 2578.61 3764.78 5716.23
River Rch & RM=6888,39,13064.93
  796.21 1388.27    1985 2581.76 3769.37  5722.6
River Rch & RM=6888,39,12824.92
  798.67 1392.75  1991.6 2590.57 3782.23 5740.42
River Rch & RM=6888,39,12584.91
  805.34 1404.92 2009.52 2614.46 3817.11 5788.68
River Rch & RM=6888,39,12288.86
 1006.49 1769.76 2544.96 3326.23 4856.29 7189.55
River Rch & RM=6888,39,12064.45
 1006.83 1770.37 2545.86 3327.42 4858.04 7191.87
River Rch & RM=6888,39,11840.05
 1012.57 1780.88 2561.39 3348.18 4888.35 7232.58
River Rch & RM=6888,39,11762.94
 1013.06 1781.78 2562.72 3349.96 4890.94 7236.07
River Rch & RM=6888,39,11434.08
 1142.19 2019.82  2915.7 3823.42 5582.19 8162.32
River Rch & RM=6888,39,10989.97
 1175.15 2080.06 3004.58  3942.1 5755.47 8389.31
River Rch & RM=6888,39,10563.34
 1178.06 2085.36 3012.37 3952.49 5770.63 8409.02
River Rch & RM=6888,39,10242.18
 1188.51  2104.4 3040.43 3989.89 5825.25 8480.08
River Rch & RM=6888,39,10064.62
 1189.64 2106.46 3043.46 3993.93 5831.14 8487.72
River Rch & RM=6888,39,9179.738
 1258.23 2230.77 3225.91 4236.42 6185.18 8942.29
River Rch & RM=6888,39,8584.131
 1307.94 2321.24 3359.08 4413.84  6444.2 9274.43
River Rch & RM=6888,39,8090.633
 1310.52 2325.91 3365.92 4422.93 6457.48 9291.29
River Rch & RM=6888,39,7597.136
 1329.48 2360.33  3416.5 4490.22 6555.71 9416.25
River Rch & RM=6888,39,7103.638
 1335.09 2370.49 3431.41 4510.03 6584.64 9452.88
River Rch & RM=6888,39,6610.141
 1485.14 2640.22 3825.35 5031.17 7345.5110397.86
River Rch & RM=6888,39,6116.643
  1511.8 2688.63 3896.53 5125.88 7483.7810570.57
River Rch & RM=6888,39,5623.146
 3497.95 6140.22 8829.79 11517.616815.69 20766.7
River Rch & RM=6888,39,5129.648
 3503.56 6150.47 8844.9311537.7916845.17 20799.7
River Rch & RM=6888,39,4636.151
 3509.12 6160.66    886011557.9116874.5420832.68
River Rch & RM=6888,39,4142.654
 3536.44  6210.9 8934.4211657.4817019.9220996.52
River Rch & RM=6888,39,1554.245
 3831.89 6746.72 9721.8512703.2318546.7222675.19
River Rch & RM=6888,39,1434.017
  3834.1  6750.8 9727.9312711.3918558.6322688.54
River Rch & RM=6888,39,1287.098
 3835.07  6752.6 9730.61   1271518563.8922694.47
River Rch & RM=6888,39, 60.2721
 3888.87 6852.37 9879.2212914.73 18855.523021.98
Boundary for River Rch & Prof#=6888,39,1
Up Type= 0
Dn Type= 2
Boundary for River Rch & Prof#=6888,39,2
Up Type= 0
Dn Type= 2
Boundary for River Rch & Prof#=6888,39,2
Up Type= 0
Dn Type= 2
Boundary for River Rch & Prof#=6888,39,2
Up Type= 0
Dn Type= 2
Boundary for River Rch & Prof#=6888,39,2
Up Type= 0
Dn Type= 2
Boundary for River Rch & Prof#=6888,39,2
Up Type= 0
Dn Type= 2

--- 6888_ras.g01 (geometry) ---

Geom Title=6888
Program Version=4.10

River Reach=6888,39
Reach XY= 30
803996.569285393720598.832955236803510.127665462720189.462546531
802374.308772684720117.872198572801098.267105996719476.379143027
800885.593494893 719274.99025414800901.218494895 719017.17775413
800812.120926711718589.479903866801110.992672592718472.116187903
801090.454878748718321.295123822801182.008487525718191.464654441
801211.424298525 717907.68955863801428.006001304717736.741176821
801687.675173401717326.125812788802160.186480851717063.166614601
802329.169883788716885.233309702802786.523796445 715926.58492682
803056.221917213715550.914546142803297.919883759715393.045809687
 803482.73369694715155.589534496804021.424732955714088.068894999
804228.475439313 713090.09442082804640.801828239712714.226365238
804562.676828238712445.997198571804751.044883788712427.768031904
804926.999874176712192.983625298805092.448787692711776.702904273
805093.926828237710834.886087459805221.010161549710019.955531906
805103.822661582709371.518031922804991.261902662709108.636674657

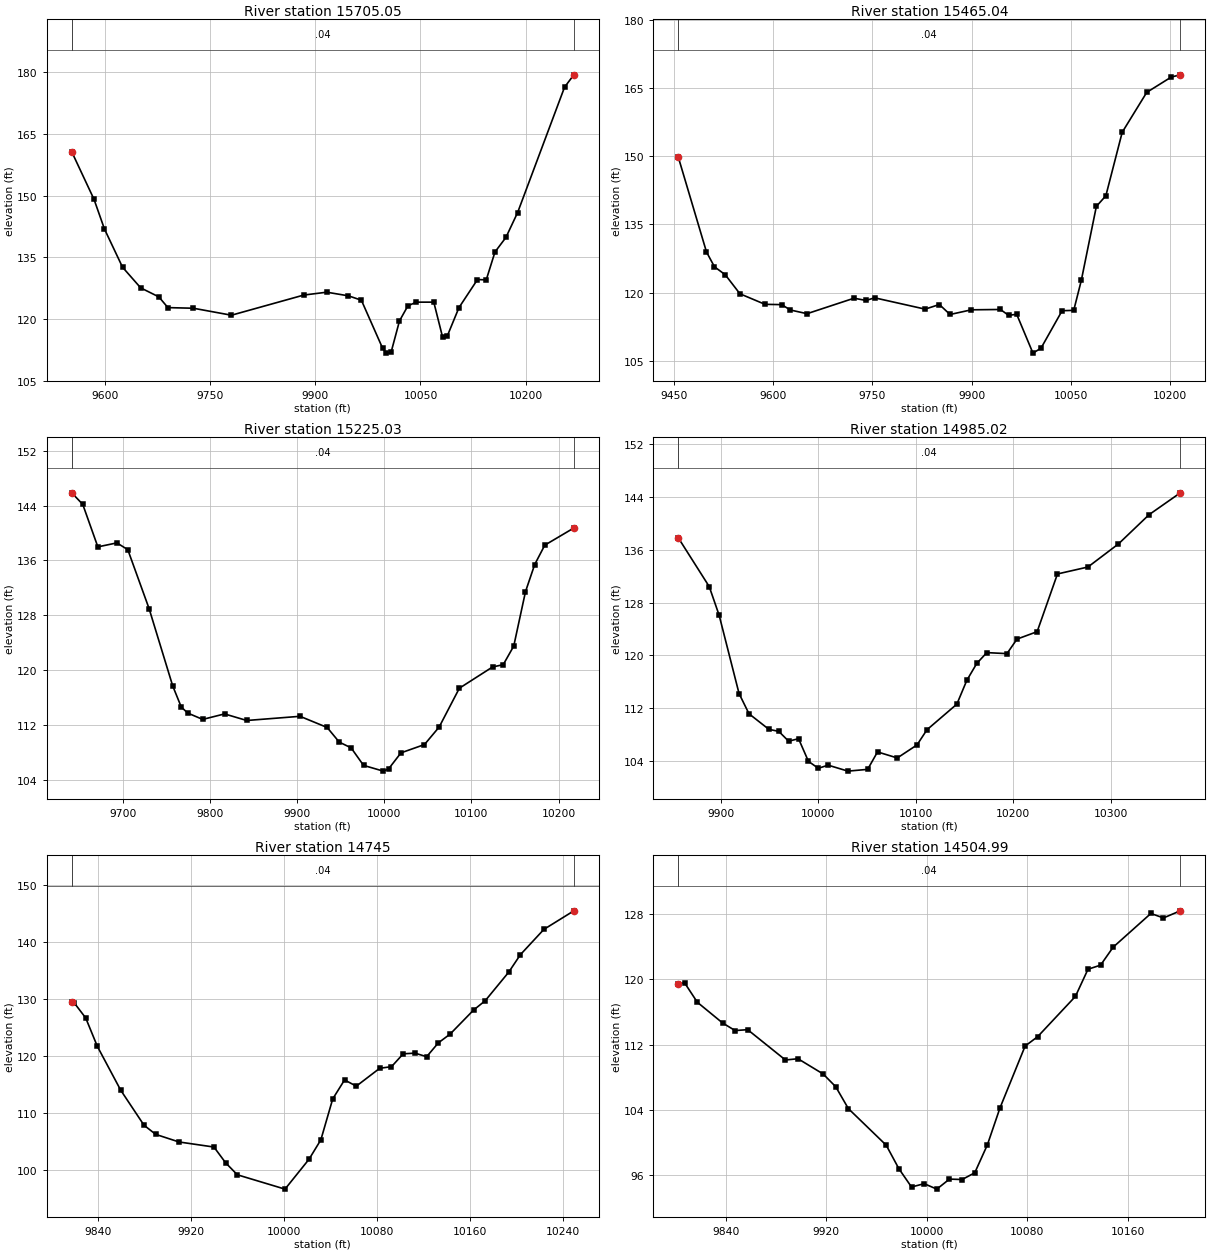
Type RM Length L Ch R = 1 ,15705.05,240.010900,240.010900,240.010900
XS GIS Cut Line= 6
804275.183353226720249.041324006804080.470332884720485.947639584
804021.321643071 720560.62352682803970.434827411 720636.22268059
803862.458689903720781.166639784803837.842385789720815.778224701
#Sta/Elev= 30
9552.517160.68449584.304149.10339599.063141.93829624.951132.6063 9650.84 127.578
9676.728125.38839689.672122.77369726.046122.62199780.282120.92529883.478125.8293
9916.301126.52679947.262125.63899965.668124.57769996.026112.862610001.35111.6978
10008.02111.883410020.05119.548510032.07 123.212 10044.1124.104110068.98124.1052
10081.45115.636610088.14 115.82510104.88122.772910131.33 129.611 10143.8129.5205
10156.27 136.31410171.84139.846410188.58 145.91410255.56176.436310268.78 179.427
#Mann= 3 , 0 , 0
9552.517    0.04       09552.517    0.04       010268.78    0.04       0
#XS Ineff= 2 , 0
       0                               0
Bank Sta=9552.517,10268.78
Exp/Cntr=0.3,0.1

Type RM Length L Ch R = 1 ,15465.04,240.011000,240.011000,240.011000
XS GIS Cut Line= 6
804148.478022107720011.205371697804058.560249719720127.633342966
803862.287644138720375.909759978803816.417358279720440.182458158
803781.559615921720490.645451122803690.334103136720616.014442827
#Sta/Elev= 30
9456.443149.87819499.143128.94469511.214125.67889527.574123.91549549.683119.7334
9587.588117.40799612.941117.34039625.688116.16489651.183115.34519722.165118.7559
9740.415118.26039753.162118.84659829.646116.34859851.164117.36879867.289115.1677
9899.539116.19939943.491116.27329955.776 114.9869968.062115.21279992.633106.6571
10004.84107.7536 10036.7115.999810054.28116.080510065.72122.673410088.48138.9835
10102.82141.320910127.55155.314710164.66164.107910201.76167.480710215.38167.9672
#Mann= 3 , 0 , 0
9456.443    0.04       09456.443    0.04       010215.38    0.04       0
#XS Ineff= 2 , 0
       0                               0
Bank Sta=9456.443,10215.38
Exp/Cntr=0.3,0.1

Type RM Length L Ch R = 1 ,15225.03,240.010900,240.010900,240.010900
XS GIS Cut Line= 6
803852.047859409720012.652208113803721.712230671720190.798262858
803683.941637779720234.868907631803573.657192161720350.063685889
803520.416822842720422.931327268803496.747914985720463.877216307
#Sta/Elev= 30
9641.633145.86289654.252144.16979671.553137.97029693.405138.55379705.895137.5625
9730.309128.96219757.408117.67269767.213114.59359774.579113.70939791.816112.7798
9816.897  113.589842.331112.6206 9903.47113.2314 9934.57111.60259948.494109.4619
9962.055108.62719976.342106.0661    9999105.227110005.06105.554510019.24107.8941
 10046.2109.106610063.04111.661610086.23117.332810124.29120.432110136.55120.7717
10148.62123.487810162.08131.425510172.65135.3937 10184.2 138.21810217.56140.7293
#Mann= 3 , 0 , 0
9641.633    0.04       09641.633    0.04       010217.56    0.04       0
#XS Ineff= 2 , 0
       0                               0
Bank Sta=9641.633,10217.56
Exp/Cntr=0.3,0.1

Type RM Length L Ch R = 1 ,14985.02,240.011000,240.011000,240.011000
XS GIS Cut Line= 6
803456.063954501720034.131485344803435.190389022720134.165610475
803412.788902365720279.756481913803399.502756474720342.534683216
803385.770638951720396.858495363803343.858309315720535.448967888
#Sta/Elev= 30
9856.583137.84119888.346130.4377 9898.55126.06889918.916114.22669929.099111.1646
9949.464108.80569959.642108.49419969.757107.00329979.872 107.3889989.987103.9614
 10000.1 102.90110010.22103.374410030.46102.471410050.69102.738510060.81105.3834
10081.05104.465110101.29106.441910111.46108.737910142.13112.627310152.35116.2387
10162.57118.801310172.81120.430810193.44120.277810203.76122.479510224.39123.6052
10245.21132.352310276.46133.405210307.72136.903210339.08141.332810371.11144.6465
#Mann= 3 , 0 , 0
9856.583    0.04       09856.583    0.04       010371.11    0.04       0
#XS Ineff= 2 , 0
       0                               0
Bank Sta=9856.583,10371.11
Exp/Cntr=0.3,0.1

Type RM Length L Ch R = 1 ,   14745,240.010900,240.010900,240.010900
XS GIS Cut Line= 6
 803217.60739516720013.037791822803209.265996373720149.445748313
803205.424740154720172.908835479803194.670006033720215.142375789
803188.466445567720247.694997234803164.049178799720440.441172926
#Sta/Elev= 30
9817.769129.53899819.735129.37549829.753126.69039839.772121.69299859.809114.0153
9879.847107.86289889.865106.25729909.903104.92169939.959104.02959949.977101.2657
 9960.0699.1574210001.0196.6413210021.65101.886810031.83105.298110042.01112.4771
10052.19115.811110062.29 114.71910082.44117.861810092.52118.135110102.59120.3949
10112.67120.515710122.74119.889210132.81 122.32610142.89 123.85610163.04128.0729
10173.11129.727610193.26134.731310203.34137.811810223.49142.242810249.23145.4988
#Mann= 3 , 0 , 0
9817.769    0.04       09817.769    0.04       010249.23    0.04       0
#XS Ineff= 2 , 0
       0                               0
Bank Sta=9817.769,10249.23
Exp/Cntr=0.3,0.1

Type RM Length L Ch R = 1 ,14504.99,240.011000,240.011000,240.011000
XS GIS Cut Line= 6
802978.895291188 719959.80815053 802970.58179045720107.286946587
 802964.48935562720157.945654171802959.250751952720202.203104752
802954.327663995720325.576753621802952.223905341720358.388566042
#Sta/Elev= 30
9802.262119.46489807.462119.54869817.478117.1978 9837.51114.66419847.526113.7262
9857.542113.83449887.589110.11569897.605110.26879917.637108.39529927.653 106.829
9937.669104.15189967.81399.659899977.88496.779799987.95494.529759998.02594.93931
 10008.194.2704610018.1795.5022310028.24 95.447310038.3196.2787410048.3799.71667
10058.37 104.23310078.39111.8238 10088.4112.981110118.42117.917610128.43121.2488
10138.44121.753910148.45123.956210178.48128.0928 10188.5127.546510201.92128.4172
#Mann= 3 , 0 , 0
9802.262    0.04       09802.262    0.04       010201.92    0.04       0
#XS Ineff= 2 , 0
       0                               0
Bank Sta=9802.262,10201.92
Exp/Cntr=0.3,0.1

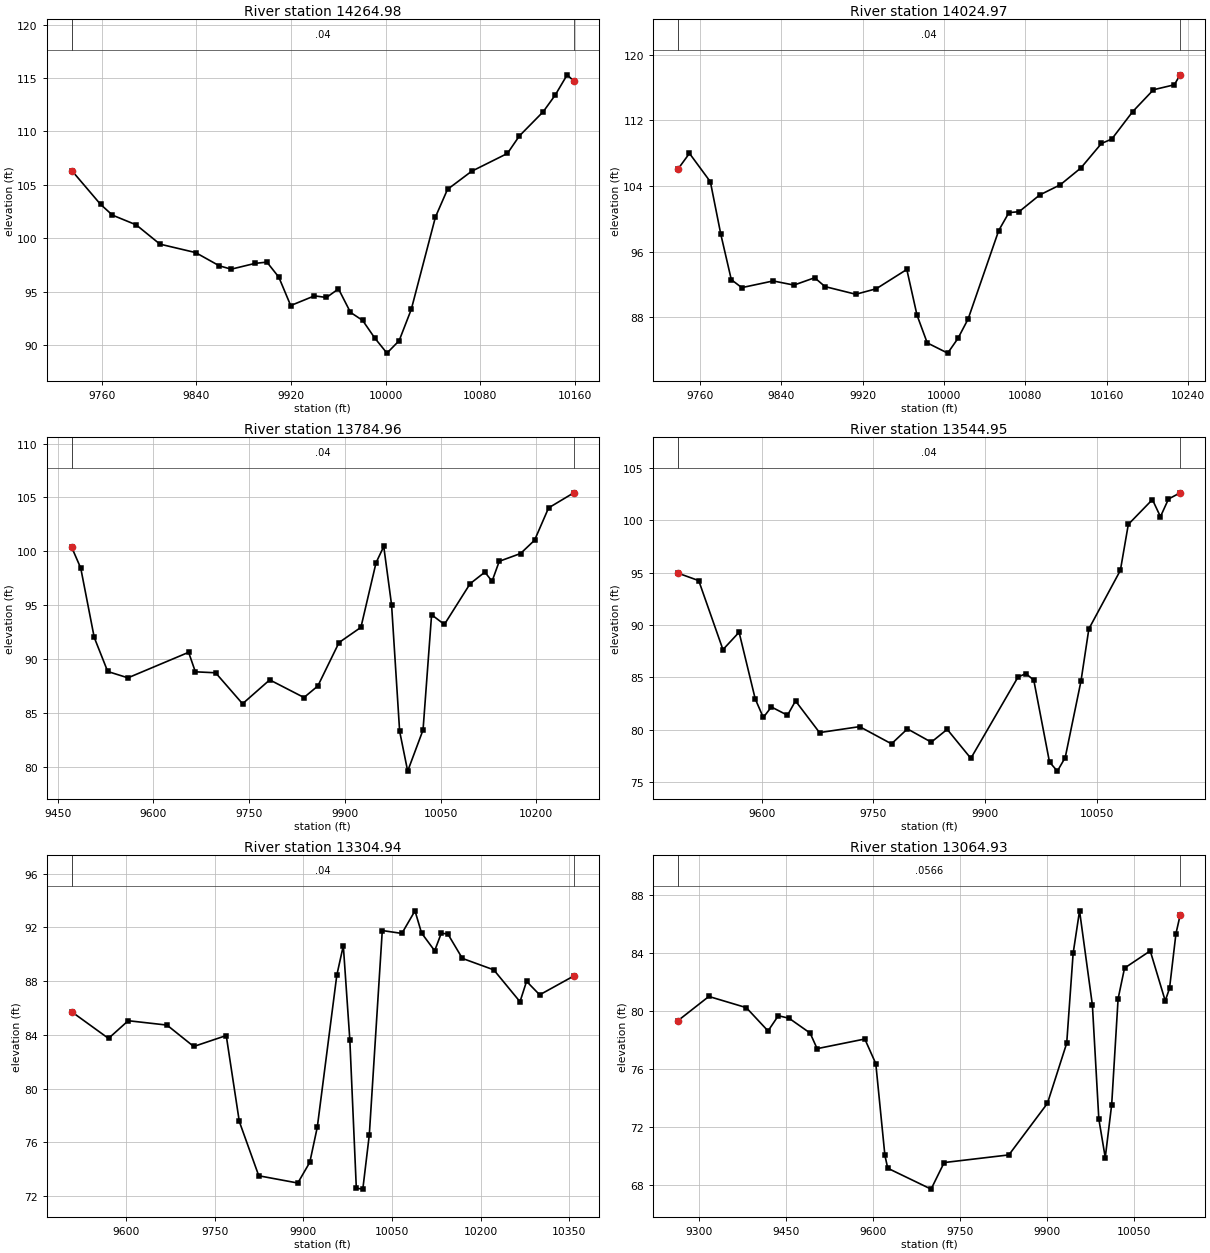
Type RM Length L Ch R = 1 ,14264.98,240.010900,240.010900,240.010900
XS GIS Cut Line= 6
802764.681850261719910.821805768802743.085021119720114.874874913
802737.510092756720146.030166994802724.534504125720199.310208366
 802716.88580985720238.002641099802702.883496582720330.502587533
#Sta/Elev= 30
9734.481106.33099758.794103.1702 9768.85102.15749788.961101.24599809.07399.43794
9839.24198.647289859.35297.404089869.40897.09239 9889.5297.634299899.57697.75328
9909.63296.346079919.68893.683029939.80194.593189949.95994.439399960.11895.24621
9970.27793.044529980.54892.292159990.83290.6372310001.1389.2263910011.4390.39155
10021.7293.3311610042.16101.981910052.35104.568410072.68106.258910103.02107.9337
10113.14109.573710133.36111.848910143.48 113.40310153.59115.300810159.16114.7213
#Mann= 3 , 0 , 0
9734.481    0.04       09734.481    0.04       010159.16    0.04       0
#XS Ineff= 2 , 0
       09880.029                       0
Bank Sta=9734.481,10159.16
Exp/Cntr=0.3,0.1

Type RM Length L Ch R = 1 ,14024.97,240.011000,240.011000,240.011000
XS GIS Cut Line= 6
802534.414823782719864.194127719802501.153007192720015.670475754
802496.642188308720061.209888264802502.479347859720152.685833708
802499.820680331720200.395002353802472.020912502720350.598466853
#Sta/Elev= 30
9738.781106.08769749.891107.98029770.454104.50919780.73598.088119791.016 92.5707
9801.29791.594829832.14192.410949852.61291.906219872.92792.802799883.08591.72213
9913.34790.786529933.44591.457199963.47693.813319973.48888.243469983.543 84.8542
10003.6583.6042110013.69 85.395310023.7287.7684610053.7898.56335 10063.8100.7493
10073.81100.8612   10094102.896710114.24104.140610134.49106.193310154.73 109.186
 10164.9109.725610185.37113.063610205.84115.739910226.31 116.34410232.04117.5602
#Mann= 3 , 0 , 0
9738.781    0.04       09738.781    0.04       010232.04    0.04       0
#XS Ineff= 2 , 0
       09905.794                       0
Bank Sta=9738.781,10232.04
Exp/Cntr=0.3,0.1

Type RM Length L Ch R = 1 ,13784.96,240.010900,240.010900,240.010900
XS GIS Cut Line= 6
802491.225025742719561.684146534802401.093195613719825.921132967
 802361.70851941719926.399251785802327.156265393719992.496550443
802225.010575028720138.689248176802162.217931798720270.923496603
#Sta/Elev= 30
9471.989100.35849486.05898.438249507.18992.007959528.32188.845929560.01888.25654
 9655.1190.625059665.67688.815349697.37388.726099739.63685.850219782.20688.06742
9835.92286.43084  9857.687.499579890.81491.531489925.13892.942119948.84198.93856
9960.916100.44869973.18995.020849985.80183.302699998.41479.5990110022.4883.41922
10035.8994.1141310055.9593.2101910096.2496.9914610119.3798.0655910130.6497.21694
10141.9299.0720310175.2999.7930310197.26 101.02710219.23104.027810258.68105.4256
#Mann= 3 , 0 , 0
9471.989    0.04       09471.989    0.04       010258.68    0.04       0
#XS Ineff= 2 , 0
       09882.569                       0
Bank Sta=9471.989,10258.68
Exp/Cntr=0.3,0.1

Type RM Length L Ch R = 1 ,13544.95,240.011000,240.011000,240.011000
XS GIS Cut Line= 6
802248.270379171719489.747002165802190.207185345 719626.42441165
802147.650470733719733.291619972802109.536193233719834.284765756
802035.226218605720050.324717194 802007.16366915720119.526340923
#Sta/Elev= 30
9487.623 94.93989515.29794.231829547.83687.641919569.52389.30171 9591.2182.93881
9602.05481.161879612.89782.165769634.58481.376839645.35982.742919677.65179.71938
9731.46980.288849774.36178.646469795.73880.073899827.80378.80541 9849.18 80.0301
9880.99877.260289944.41385.027089954.98285.351719965.55284.73121 9986.6976.90508
9997.25976.0397910007.8177.3383310028.9984.6360310039.5889.6209510081.9395.21122
10092.6199.6011110124.99101.970210135.78100.334510146.57102.022410162.24102.6149
#Mann= 3 , 0 , 0
9487.623    0.04       09487.623    0.04       010162.24    0.04       0
#XS Ineff= 2 , 0
       09950.277                       0
Bank Sta=9487.623,10162.24
Exp/Cntr=0.3,0.1

Type RM Length L Ch R = 1 ,13304.94,240.010900,240.010900,240.010900
XS GIS Cut Line= 6
802057.572214477719419.293836062802053.699454691719426.442664401
801986.295557611719563.902754043801826.976041607719909.909387762
801717.382902636720136.060048564801691.654072354720186.376994345
#Sta/Elev= 30
9507.882 85.70739570.09383.729729603.50585.047789669.10984.721879714.36983.12865
9769.43483.943369791.55277.545089824.49973.502899890.57772.963489910.90274.50487
9923.61677.122919956.65588.437069967.66890.634129978.68183.632749989.69472.57758
10000.6972.5086510011.6776.5457910033.6591.76117 10066.891.5463510089.0393.22895
10100.1491.5760110122.3690.2549910133.4891.5552110144.5991.5117810169.2289.68725
10222.38 88.835610266.8386.4603210277.94 87.978310300.1686.9744410357.8588.37658
#Mann= 3 , 0 , 0
9507.882    0.04       09507.882    0.04       010357.85    0.04       0
#XS Ineff= 2 , 0
       09966.987                       0
Bank Sta=9507.882,10357.85
Exp/Cntr=0.3,0.1

Type RM Length L Ch R = 1 ,13064.93,240.011000,240.011000,240.011000
XS GIS Cut Line= 6
802002.205542078719134.723318927801907.556147999719251.108335899
801850.712638018 719335.09902069801807.439206143719406.887204258
801725.982234872 719560.44328543801574.005261662719881.508821168
#Sta/Elev= 30
9264.52279.352739317.42781.011739381.87180.240919419.29678.634099436.99979.68301
 9455.5279.510059491.74578.48843 9503.8277.413939585.95778.079099604.86176.38157
9620.55470.054299625.46269.173249700.08967.732879722.57969.563869834.03270.09139
9900.40573.645529933.59177.789889944.65383.979899955.71586.913089977.83980.40584
9988.901 72.56679999.96369.9041210011.0373.55738 10022.180.8540510033.1682.96634
10077.4384.1528110103.2380.7111710110.6381.56819 10121.785.34224 10128.986.60948
#Mann= 3 , 0 , 0
9264.522  0.0566       09264.522  0.0566       0 10128.9  0.0566       0
#XS Ineff= 2 , 0
       09960.986                       0
Bank Sta=9264.522,10128.9
Exp/Cntr=0.3,0.1

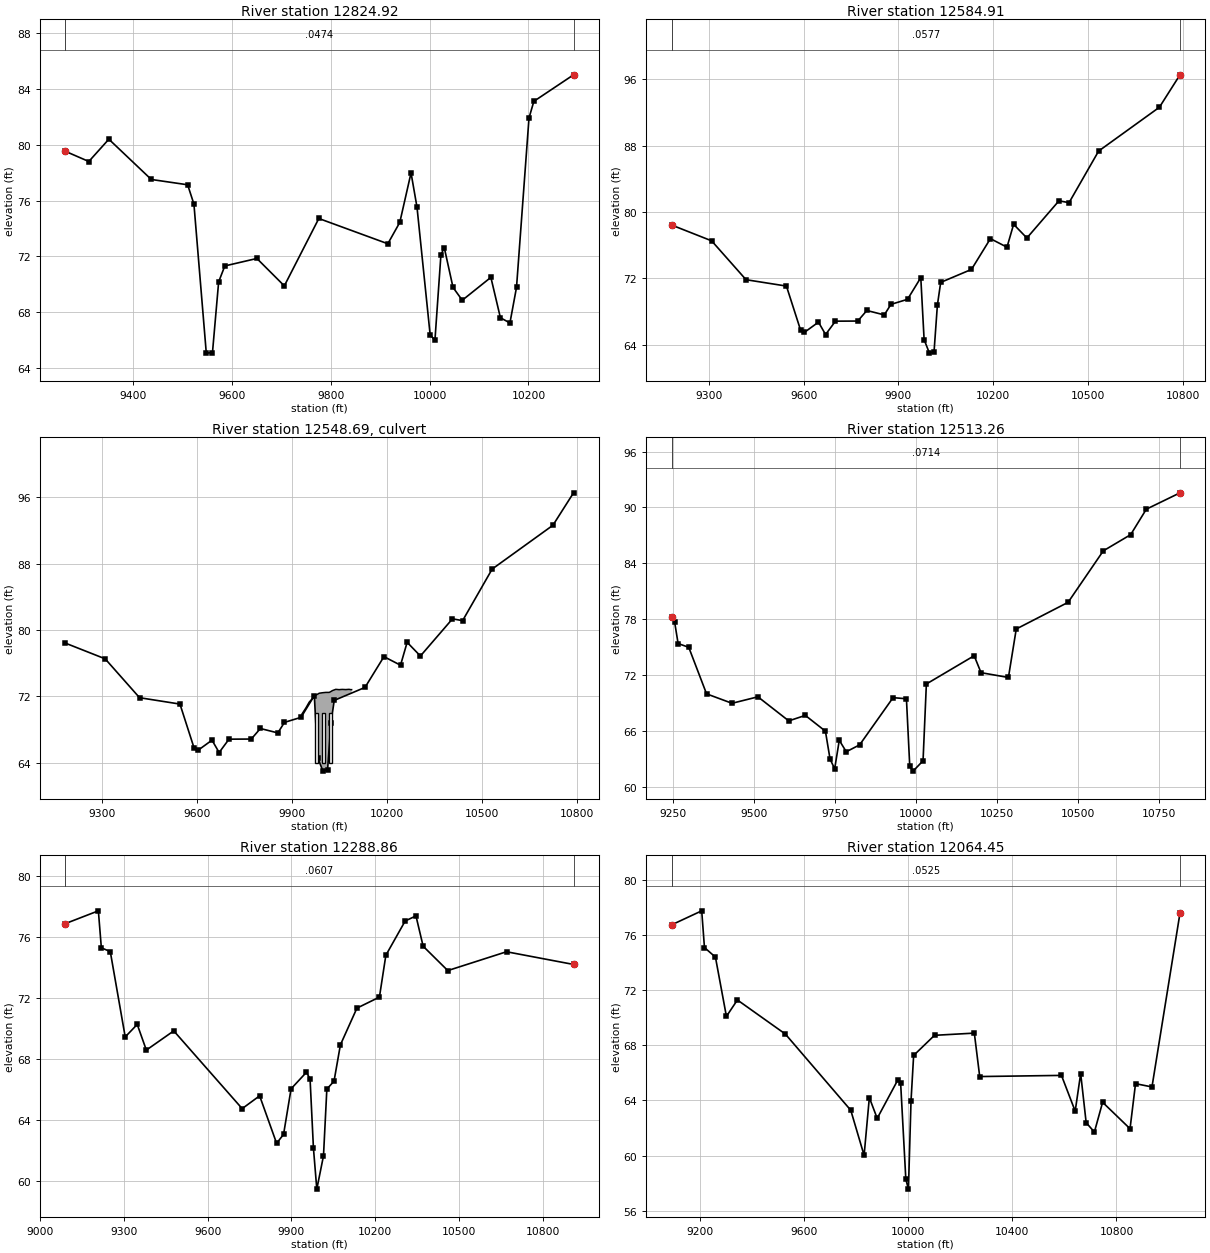
Type RM Length L Ch R = 1 ,12824.92,240.010900,240.010900,240.010900
XS GIS Cut Line= 6
801851.352424524719079.550207458801739.794488164719182.926940936
801673.273397063719259.468837068 801622.95785845719326.504036521
801568.008784025719409.165341757801257.549911286  719913.2327883
#Sta/Elev= 30
9262.41579.534269310.18478.799129350.73780.395259436.67377.512229510.23477.13232
9522.96275.745679547.96965.081529560.47365.119539572.97670.18188 9585.48 71.3229
9650.36671.857959705.91369.895369775.73974.71941 9915.3972.910399939.608 74.4399
9962.38477.984329974.45375.52938   1000166.4104610010.7365.9882410022.8272.09811
10029.58 72.642810047.3869.7818810066.0968.8676410123.9670.5047810143.2567.61586
10162.54 67.240810175.8769.7909210201.1281.9106210210.96 83.107510291.2785.00363
#Mann= 3 , 0 , 0
9262.415  0.0474       09262.415  0.0474       010291.27  0.0474       0
#XS Ineff= 2 , 0
       09952.161        10040.55       0
Bank Sta=9262.415,10291.27
Exp/Cntr=0.3,0.1

Type RM Length L Ch R = 1 ,12584.91,71.646500,71.646500,71.646500
XS GIS Cut Line= 6
801795.539344698719033.889177114801764.861389279719053.724665612
801288.411804825719300.265290633801203.342360407719567.626401767
801116.546217859719844.088189095800754.123610407720134.249665648
#Sta/Elev= 30
9182.82978.440569309.17476.53832 9417.9771.85014 9545.7371.081629590.76865.73928
9602.02765.484549647.06566.731459669.58465.238819700.84366.849669771.28166.86347
9800.05268.136119855.23367.603799876.22168.873879928.69169.483949970.66772.09989
9981.16164.625219997.939 62.995110012.6463.1903910023.1468.7843110033.6371.52487
10131.0173.0935710190.8576.8016810243.2675.7707110264.2278.5311810306.1576.87902
10407.6181.3628210439.6181.14204 10533.1 87.364710725.2592.6462410790.4296.55819
#Mann= 3 , 0 , 0
9182.829  0.0577       09182.829  0.0577       010790.42  0.0577       0
#XS Ineff= 2 , 0
       09944.563                       0
Bank Sta=9182.829,10790.42
Exp/Cntr=0.3,0.1

Type RM Length L Ch R = 2 ,12548.69,,,
Bridge Culvert--1,0,-1,-1, 0
Deck Dist Width WeirC Skew NumUp NumDn MinLoCord MaxHiCord MaxSubmerge Is_Ogee
15.823,40,2.6,0,22,22, , , 0.95, 0, 0,0,,
 9931.38 9933.72 9944.20 9954.34 9954.69 9965.17 9975.65 9986.14 9987.64 9996.62
10007.1110017.5910020.9410028.0710038.5610049.0410054.2410059.5310070.0110080.49
10087.5410088.64
   69.87   70.01   70.63   71.31   71.33   71.77   72.16   72.39   72.40   72.45
   72.49   72.49   72.55   72.71   72.86   72.82   72.84   72.85   72.83   72.86
   72.81   72.82
                                                                                
                                                                                
                
 9931.38 9933.72 9944.20 9954.34 9954.69 9965.17 9975.65 9986.14 9987.64 9996.62
10007.1110017.5910020.9410028.0710038.5610049.0410054.2410059.5310070.0110080.49
10087.5410088.64
   69.87   70.01   70.63   71.31   71.33   71.77   72.16   72.39   72.40   72.45
   72.49   72.49   72.55   72.71   72.86   72.82   72.84   72.85   72.83   72.86
   72.81   72.82
                                                                                
                                                                                
                
BR Coef=-1 , 0 , 0 ,, 0 ,,,0.8,-1,,0,
WSPro=,,,, 1 ,,,, 0 ,,,, 0 ,,,,-1 ,-1 ,-1 , 0 , 0 , 0 , 0 , 0
Multiple Barrel Culv=2,6,11,40,0.013,0.5,1,8,3,64,62,3,Culvert #1, 0, 15.823
 9978.00 9978.0010000.0010000.0010022.0010022.00
Culvert Bottom n=0.013
BC Design=,, 0 ,, 0 ,,,,,,

Type RM Length L Ch R = 1 ,12513.26,224.404300,224.404300,224.404300
XS GIS Cut Line= 6
801643.105566353719005.456520855 801373.04361847719142.652323917
801203.959711552719277.451231733801139.106249273719548.529179528
801053.385763168719802.652443409800638.889235407720081.515290633
#Sta/Elev= 30
9247.03678.202479255.90677.738819266.84975.384329299.67774.978289354.51869.98083
9432.99468.96803 9512.84 69.66299607.86667.078469658.89767.66817 9720.8465.97085
9735.075 62.98489749.31161.929179763.54764.994269785.10963.763169826.30464.50552
9929.29269.573159970.487 69.4532 9980.7462.210969990.97861.6834410021.6962.79615
10031.9371.0395310179.2574.0739910200.3672.2545710284.7971.7404610308.9276.94386
10468.7179.8094610577.1885.3361510661.5587.0749810709.7689.8083710813.5491.56566
#Mann= 3 , 0 , 0
9247.036  0.0714       09247.036  0.0714       010813.54  0.0714       0
#XS Ineff= 2 , 0
       09930.258                       0
Bank Sta=9247.036,10813.54
Exp/Cntr=0.3,0.1

Type RM Length L Ch R = 1 ,12288.86,224.404400,224.404400,224.404400
XS GIS Cut Line= 6
801746.335146762718949.327673307801395.014718706719086.981513555
 801092.40385825719252.169011972801009.188116679719319.552371643
800760.842196807719587.280089264800256.395424405719951.869676281
#Sta/Elev= 30
9090.38776.863859209.07177.706569219.73175.277929251.71175.032959305.13169.43281
9348.16370.253349380.72968.568169478.92269.828779723.71464.727269786.22265.56805
9846.953  62.4539871.82463.03593 9898.7766.028719953.93267.117699966.75366.65581
9978.78462.137819990.81659.4460810014.77  61.63210026.7766.0088910052.4566.52966
10075.2568.9102410134.3971.3212310214.9572.0468710237.9374.7878510307.2577.04343
10345.7277.3719310371.3875.3841510459.6273.7858910669.7775.0213910909.6474.18795
#Mann= 3 , 0 , 0
9090.387  0.0607       09090.387  0.0607       010909.64  0.0607       0
#XS Ineff= 2 , 0
       09867.485                       0
Bank Sta=9090.387,10909.64
Exp/Cntr=0.3,0.1

Type RM Length L Ch R = 1 ,12064.45,224.404300,224.404300,224.404300
XS GIS Cut Line= 6
801744.403529853718940.892339781801099.700374156719167.993379787
800991.803108484719186.745986715800786.118816584719190.181237057
800667.918055058719210.362368017799872.819356948 719464.73288323
#Sta/Elev= 30
9090.05176.731059205.51877.745729216.073 75.0851 9258.2974.389539300.50770.09551
9342.72471.285219527.16468.813389778.54863.29238  9829.860.023929849.94664.20627
9880.16462.705339960.21365.516689970.21565.27866 9990.2258.2906210000.23  57.576
10010.2363.9910310020.2367.2647110100.4468.7227910253.5568.8827910274.2265.73463
10588.5665.8181910641.2863.2253310662.3665.9500510683.45 62.395310715.0861.71074
10746.7163.8704910852.1461.9538110873.2265.2201310936.4864.9810111044.2177.58722
#Mann= 3 , 0 , 0
9090.051  0.0525       09090.051  0.0525       011044.21  0.0525       0
#XS Ineff= 2 , 0
       09816.685        10084.49       0
Bank Sta=9090.051,11044.21
Exp/Cntr=0.3,0.1

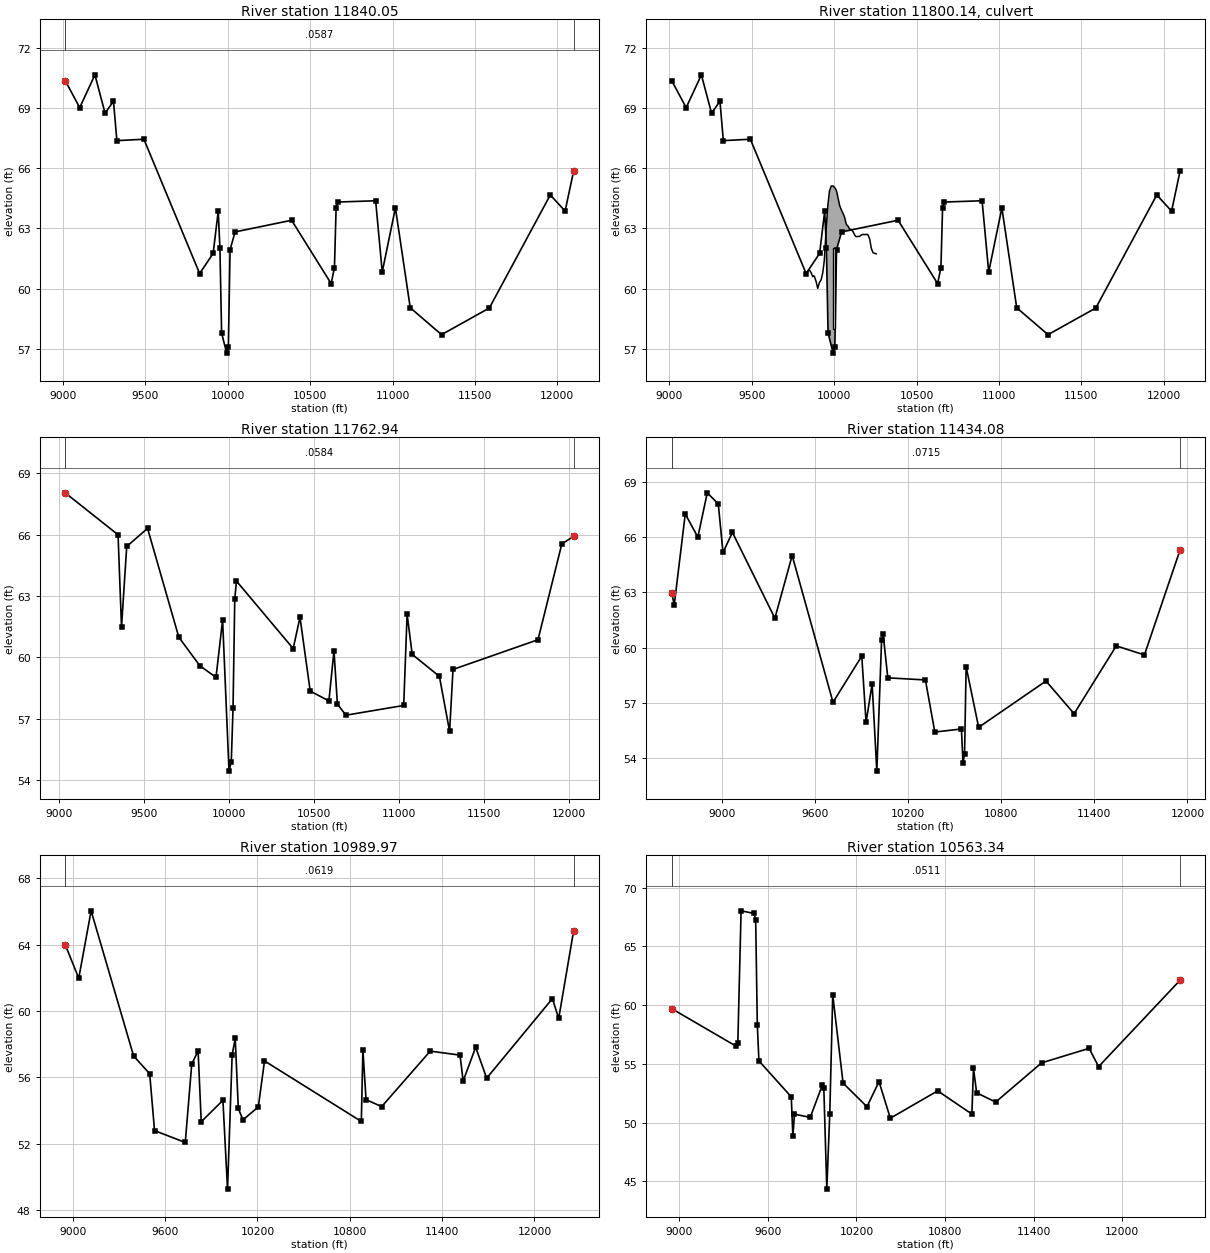
Type RM Length L Ch R = 1 ,11840.05,77.111100,77.111100,77.111100
XS GIS Cut Line= 6
801850.911804825718751.654179528800981.120138228718947.834735096
800863.356233507718975.067638054800685.981249273718940.890290633
799911.073794633718943.785800904 798793.91382435718935.528406337
#Sta/Elev= 30
9013.39170.365799101.46169.017769193.72170.653889255.22968.743259306.48569.33548
9326.98767.373669491.00667.444039829.29660.748979911.31461.753549942.10563.85825
9952.36962.038729962.633 57.78719993.42556.7824210003.6957.1012710013.9561.93832
 10044.662.8238310387.5263.4055310627.5360.2472510647.5361.0438110657.5363.99892
10667.5364.3132510897.5364.3759810937.5360.8247911017.5364.0223411107.5359.04463
11297.54 57.703311587.54 59.029811957.5564.6659912047.5663.8622612098.6465.84268
#Mann= 3 , 0 , 0
9013.391  0.0587       09013.391  0.0587       012098.64  0.0587       0
#XS Ineff= 2 , 0
       09684.858        10027.82       0
Bank Sta=9013.391,12098.64
Exp/Cntr=0.3,0.1

Type RM Length L Ch R = 2 ,11800.14,,,
Bridge Culvert--1,0,-1,-1, 0
Deck Dist Width WeirC Skew NumUp NumDn MinLoCord MaxHiCord MaxSubmerge Is_Ogee
16.056,45,2.6,0,55,55, , , 0.95, 0, 0,0,,
 9822.12 9823.88 9828.26 9838.54 9848.82 9859.11 9866.88 9869.39 9873.44 9879.58
 9882.62 9889.72 9899.86 9910.01 9920.15 9930.29 9936.91 9940.48 9950.78 9961.07
 9971.37 9974.81 9981.66 9991.9610002.2510012.5510016.8710022.8410032.7210033.13
10043.2310053.3410059.0510063.4410073.5510083.6510093.7510103.8610113.9610124.07
10128.9410134.1710144.2710154.3810164.4810174.5910184.6910194.7910198.8310204.90
10215.0010225.1110235.2110245.3110254.78
   60.71   60.71   60.69   60.87   60.93   60.80   60.65   60.59   60.64   60.61
   60.53   60.36   60.01   60.30   60.43   60.78   61.20   61.48   62.95   64.13
   64.88   64.95   65.11   65.12   65.04   64.90   64.76   64.53   64.15   64.14
   63.92   63.75   63.64   63.54   63.20   63.11   62.96   62.94   62.84   62.67
   62.62   62.58   62.60   62.60   62.67   62.70   62.69   62.70   62.70   62.68
   62.47   62.01   61.79   61.76   61.73
                                                                                
                                                                                
                                                                                
                                                                                
                                                                                
                                        
 9822.12 9823.88 9828.26 9838.54 9848.82 9859.11 9866.88 9869.39 9873.44 9879.58
 9882.62 9889.72 9899.86 9910.01 9920.15 9930.29 9936.91 9940.48 9950.78 9961.07
 9971.37 9974.81 9981.66 9991.9610002.2510012.5510016.8710022.8410032.7210033.13
10043.2310053.3410059.0510063.4410073.5510083.6510093.7510103.8610113.9610124.07
10128.9410134.1710144.2710154.3810164.4810174.5910184.6910194.7910198.8310204.90
10215.0010225.1110235.2110245.3110254.78
   60.71   60.71   60.69   60.87   60.93   60.80   60.65   60.59   60.64   60.61
   60.53   60.36   60.01   60.30   60.43   60.78   61.20   61.48   62.95   64.13
   64.88   64.95   65.11   65.12   65.04   64.90   64.76   64.53   64.15   64.14
   63.92   63.75   63.64   63.54   63.20   63.11   62.96   62.94   62.84   62.67
   62.62   62.58   62.60   62.60   62.67   62.70   62.69   62.70   62.70   62.68
   62.47   62.01   61.79   61.76   61.73
                                                                                
                                                                                
                                                                                
                                                                                
                                                                                
                                        
BR Coef=-1 , 0 , 0 ,, 0 ,,,0.8,-1,,0,
WSPro=,,,, 1 ,,,, 0 ,,,, 0 ,,,,-1 ,-1 ,-1 , 0 , 0 , 0 , 0 , 0
Culvert=2,4,11,45,0.013,0.5,1,8,3,58,10000,56,10000,Culvert #1, 0, 16.056
Culvert Bottom n=0.013
BC Design=,, 0 ,, 0 ,,,,,,

Type RM Length L Ch R = 1 ,11762.94,328.854200,328.854200,328.854200
XS GIS Cut Line= 6
801809.245138168718689.154179528801159.939582616718824.570846215
800831.758442283718902.741954759800665.147915959718869.709735096
 799872.03882435718854.799239695798845.997157693718849.590906337
#Sta/Elev= 30
9034.83468.038489345.62565.989849366.05561.486619396.701 65.41979519.28366.30098
9703.20760.982679827.037 59.58889921.89759.022489960.69661.822299998.38154.44164
10011.81 54.900410022.0357.5232110032.2662.8695910042.3663.7272310375.91 60.4285
10415.9261.9614210475.9358.3538110585.9557.8709210615.95 60.322510635.9657.71575
10685.97 57.173511026.0257.6500611046.0262.1067411076.02 60.146811236.0259.06973
11296.0256.3849411316.0359.4087911816.0360.8622211956.0365.5394512025.0465.90989
#Mann= 3 , 0 , 0
9034.834  0.0584       09034.834  0.0584       012025.04  0.0584       0
#XS Ineff= 2 , 0
       09611.927        10042.07       0
Bank Sta=9034.834,12025.04
Exp/Cntr=0.3,0.1

Type RM Length L Ch R = 1 ,11434.08,444.106400,444.106400,444.106400
XS GIS Cut Line= 6
802071.397915959718610.595151767801196.397915959718753.824318409
801021.918749303718727.782651767800849.520222038718587.406006813
800786.508662403718571.960746303798877.247157693718815.736739695
#Sta/Elev= 30
 8676.2262.968778692.83662.327828763.76867.262188844.83366.006678905.63168.41098
8976.56367.811819006.962 65.1736 9067.7666.261339341.35461.601129452.81865.00561
 9715.9457.033789901.34859.542419929.05555.943319968.08958.031139998.36753.29564
10028.9360.3928110039.02 60.7215 10069.358.36207 10311.558.2483410372.0555.41927
10543.6155.58441 10553.753.7423410563.7954.2397210573.8958.9661810654.6255.67543
11088.5658.18987 11269.8 56.415111541.6760.0984711722.9259.6061311952.2465.29974
#Mann= 3 , 0 , 0
 8676.22  0.0715       0 8676.22  0.0715       011952.24  0.0715       0
#XS Ineff= 2 , 0
       09481.852        10035.11       0
Bank Sta=8676.22,11952.24
Exp/Cntr=0.3,0.1

Type RM Length L Ch R = 1 ,10989.97,426.633900,426.633900,426.633900
XS GIS Cut Line= 6
802132.777398854718584.739981756801814.348683089718544.894537836
801299.823512018718390.538634315801183.550693721718372.921540633
800748.687412471718388.343994364798890.267991006718742.820073023
#Sta/Elev= 30
8950.43963.99891 9038.36 61.97079118.80266.037839395.06757.280629499.46956.21383
9530.99852.781399730.68552.066049772.65256.784969814.08257.60081 9834.3153.31617
9975.35854.6076210005.3649.2520510035.3657.3551810055.3858.33994 10075.454.11559
10105.4353.4297310205.5254.2102710245.5656.9844410874.8253.33335   1088557.66337
10905.37   54.6511007.1954.2302811322.7957.5761511516.1957.3344711536.5555.77412
11617.9857.8112311689.2455.9419912116.7660.7444312157.4759.54359 12253.964.79985
#Mann= 3 , 0 , 0
8950.439  0.0619       08950.439  0.0619       0 12253.9  0.0619       0
#XS Ineff= 2 , 0
       09796.445        10046.22       0
Bank Sta=8950.439,12253.9
Exp/Cntr=0.3,0.1

Type RM Length L Ch R = 1 ,10563.34,321.162600,321.162600,321.162600
XS GIS Cut Line= 6
802162.607170433718360.855385423801288.820593745718002.473039672
801151.001230717717980.719485715801012.543749273717985.334735081
800363.738851845718112.871877566798911.101324379718677.715906367
#Sta/Elev= 30
8948.63259.708899385.82556.508219396.81356.822319418.78768.031649506.68567.81006
9517.67267.254499528.65958.346229539.64755.26507 9758.8452.199139769.643 48.8284
9780.44650.727079887.39650.45495  9969.353.206749979.34952.923779999.44644.34982
10019.5850.7801510039.6860.8760610109.7253.3708310271.6251.3629710353.1553.49995
 10429.750.3837910750.6152.7118310982.2950.7350410993.0254.6325611014.4752.54723
11143.2351.7578511454.38 55.093611776.2656.3307211840.64  54.77512392.0262.11735
#Mann= 3 , 0 , 0
8948.632  0.0511       08948.632  0.0511       012392.02  0.0511       0
#XS Ineff= 2 , 0
       09682.661        10046.91       0
Bank Sta=8948.632,12392.02
Exp/Cntr=0.3,0.1