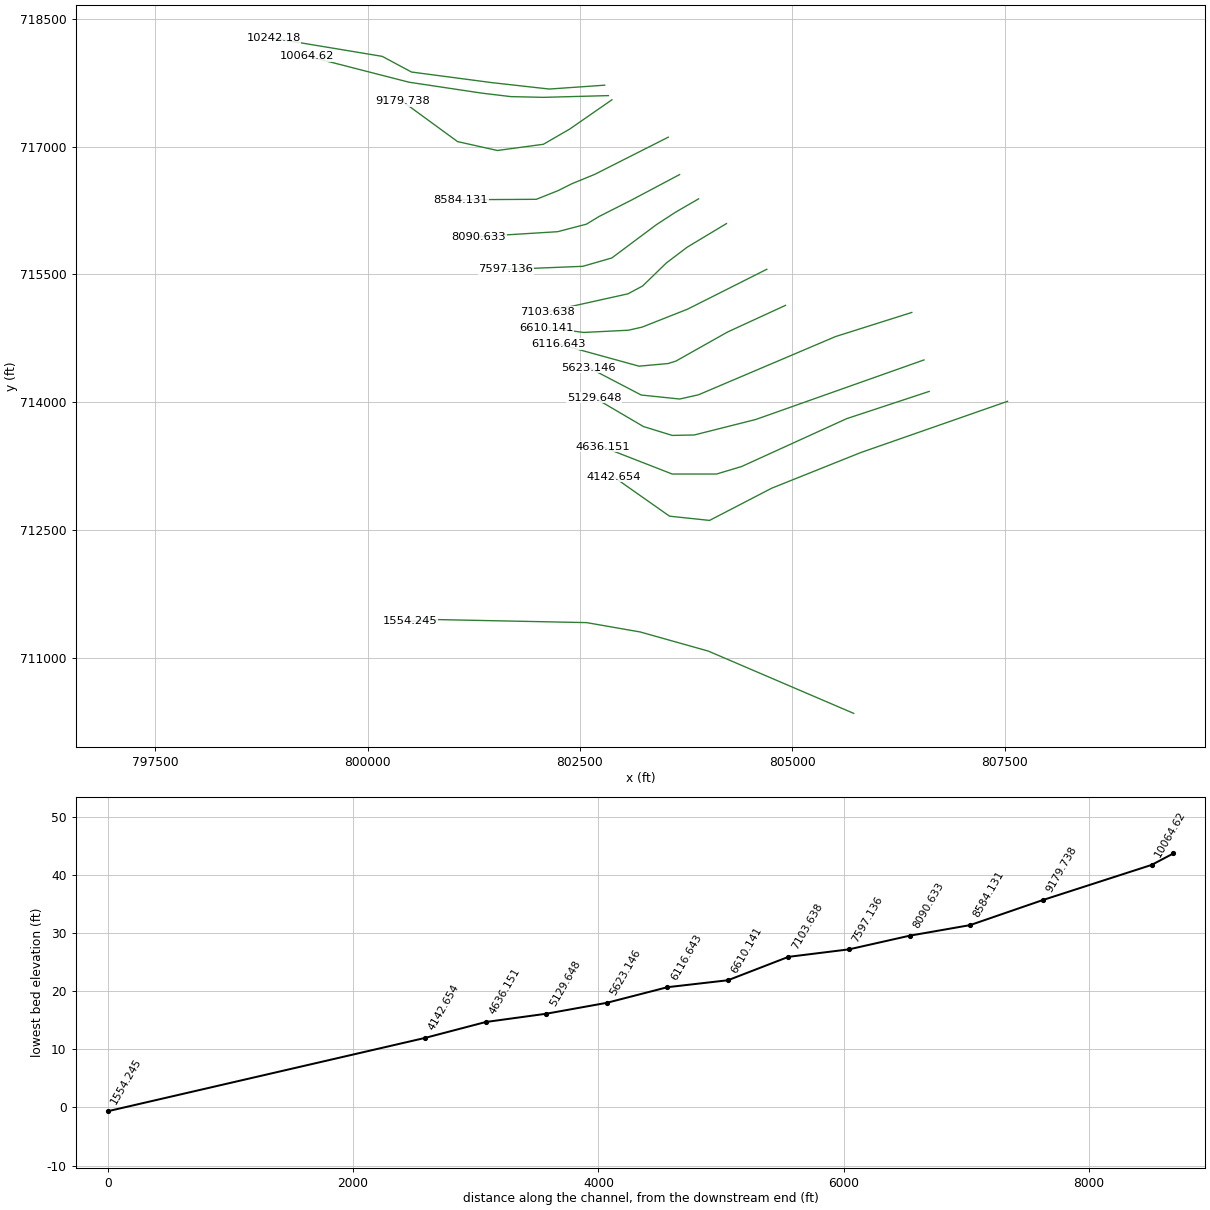
HEC-RAS study 6888_ras.prj: 6888

--- 6888_ras.g01 (geometry) --- (continued)

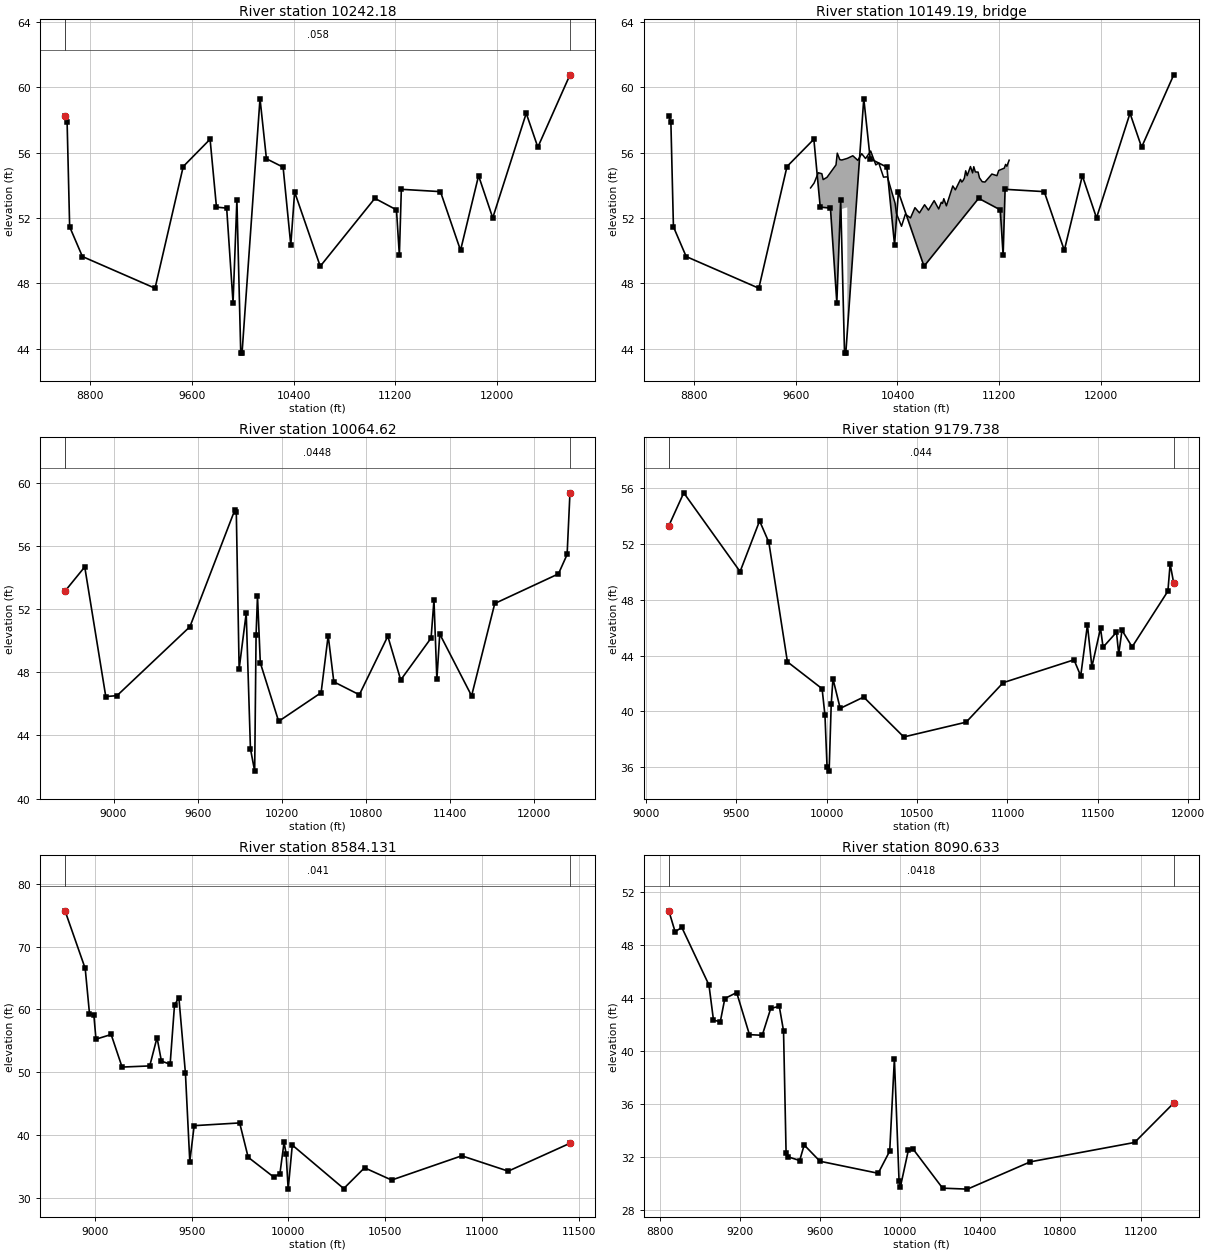
Type RM Length L Ch R = 1 ,10242.18,177.555400,177.555400,177.555400
XS GIS Cut Line= 6
802791.222134709717721.677327693 802139.60538125717676.306957304
801462.522047907717751.827790648800516.925399542717876.234928459
800173.582787812718059.858912468798895.476324379718271.465906352
#Sta/Elev= 30
8600.50758.246968616.76957.882688636.81751.459668737.05949.635739308.76347.69475
  9530.6 55.15119741.83556.822719792.04152.663619872.37152.602169922.57746.80816
9952.813 53.09629983.12743.732029993.23243.71748 10134.759.3118110185.2255.62606
10316.4455.11187 10376.950.3444910407.1353.5906810608.6749.03882 11038.553.20166
11208.6152.4950311231.2949.7089311246.7553.7547711554.6253.6123611712.6750.01458
11854.5854.5872711966.0852.0037212229.6258.4130412320.8456.3355412573.7660.76897
#Mann= 3 , 0 , 0
8600.507   0.058       08600.507   0.058       012573.76   0.058       0
#XS Ineff= 2 , 0
       09939.442         10028.4       0
Bank Sta=8600.507,12573.76
Exp/Cntr=0.3,0.1

Type RM Length L Ch R = 3 ,10149.19,,,
BEGIN DESCRIPTION:
END DESCRIPTION:
Bridge Culvert--1,0,-1,-1, 0
Deck Dist Width WeirC Skew NumUp NumDn MinLoCord MaxHiCord MaxSubmerge Is_Ogee
51.777700,74.000000,2.6,0, 60, 60, , , 0.95, 0, 0,0,,
 9716.00 9744.13 9776.40 9804.79 9814.90 9845.22 9915.99 9926.10 9946.32 9961.93
 9961.9310004.9310004.9310048.4510087.8610118.1910148.5210188.9610229.4010252.48
10290.0610320.4910381.0510391.1610431.5510461.8110502.1710537.3810572.7910613.15
10643.4210688.3310724.1310744.3010754.3910764.4810784.6610835.1110855.2810895.64
10905.7310915.8210926.0110936.7310948.1610974.2010990.8811000.2411012.5411034.21
11045.0411066.7011088.3611142.5111182.4811196.6711239.9911250.8211260.5911278.57
   53.84   54.14   54.77   54.71   54.35   54.49   55.25   55.97   55.57   55.55
   55.55   55.65   55.65   55.81   55.53   55.94   55.64   56.10   55.25   55.37
   54.50   54.52   52.90   52.28   51.49   52.23   52.00   52.63   52.31   52.81
   52.48   53.06   52.55   52.96   52.89   53.18   52.74   53.96   53.72   54.36
   54.20   54.29   54.44   54.89   54.59   55.15   54.76   55.14   54.82   54.81
   54.46   54.22   54.20   54.69   54.59   54.91   55.05   55.28   55.17   55.54
 -946.16 -945.86 -945.23 -945.29 -945.65 -945.51 -944.75 -944.03 -944.43 -944.45
   52.55   52.65 -944.35 -944.19 -944.47 -944.06 -944.36 -943.90 -944.75 -944.63
 -945.50 -945.48 -947.10 -947.72 -948.51 -947.77 -948.00 -947.37 -947.69 -947.19
 -947.52 -946.94 -947.45 -947.04 -947.11 -946.82 -947.26 -946.04 -946.28 -945.64
 -945.80 -945.71 -945.56 -945.11 -945.41 -944.85 -945.24 -944.86 -945.18 -945.19
 -945.54 -945.78 -945.80 -945.31 -945.41 -945.09 -944.95 -944.72 -944.83 -944.46
 9716.00 9744.13 9776.40 9804.79 9814.90 9845.22 9915.99 9926.10 9946.32 9969.37
 9969.3710012.3710012.3710048.4510087.8610118.1910148.5210188.9610229.4010252.48
10290.0610320.4910381.0510391.1610431.5510461.8110502.1710537.3810572.7910613.15
10643.4210688.3310724.1310744.3010754.3910764.4810784.6610835.1110855.2810895.64
10905.7310915.8210926.0110936.7310948.1610974.2010990.8811000.2411012.5411034.21
11045.0411066.7011088.3611142.5111182.4811196.6711239.9911250.8211260.5911278.57
   53.84   54.14   54.77   54.71   54.35   54.49   55.25   55.97   55.57   55.57
   55.57   55.66   55.66   55.81   55.53   55.94   55.64   56.10   55.25   55.37
   54.50   54.52   52.90   52.28   51.49   52.23   52.00   52.63   52.31   52.81
   52.48   53.06   52.55   52.96   52.89   53.18   52.74   53.96   53.72   54.36
   54.20   54.29   54.44   54.89   54.59   55.15   54.76   55.14   54.82   54.81
   54.46   54.22   54.20   54.69   54.59   54.91   55.05   55.28   55.17   55.54
 -946.16 -945.86 -945.23 -945.29 -945.65 -945.51 -944.75 -944.03 -944.43 -944.43
   52.57   52.66 -944.34 -944.19 -944.47 -944.06 -944.36 -943.90 -944.75 -944.63
 -945.50 -945.48 -947.10 -947.72 -948.51 -947.77 -948.00 -947.37 -947.69 -947.19
 -947.52 -946.94 -947.45 -947.04 -947.11 -946.82 -947.26 -946.04 -946.28 -945.64
 -945.80 -945.71 -945.56 -945.11 -945.41 -944.85 -945.24 -944.86 -945.18 -945.19
 -945.54 -945.78 -945.80 -945.31 -945.41 -945.09 -944.95 -944.72 -944.83 -944.46
BR Coef=-1 , 0 , 0 ,, 0 ,,,0.8,0,1,0,
WSPro=,,,, 1 ,,,, 0 ,,,, 0 ,,,,-1 ,-1 ,-1 , 0 , 0 , 0 , 0 , 0
BC Design=,, 0 ,, 0 ,,,,,,

Type RM Length L Ch R = 1 ,10064.62,884.885300,884.885300,884.885300
XS GIS Cut Line= 6
802835.492968082717599.281494364802069.177140534717578.911123976
801685.496584982717587.591679558801338.274362683717629.258346215
800485.959547907717757.036123976799285.245040894718064.337092608
#Sta/Elev= 30
8653.95153.142948794.49454.677028944.54746.463139024.57546.521769544.74550.88858
9865.41358.291649875.51258.16025 9895.7148.212869946.20651.749059976.40143.15719
10006.5641.7408510016.6250.3672710026.6752.8277210046.7848.6000210177.5844.89485
10480.3546.7075210530.8150.3250510571.1847.3965810753.0746.5784310956.1350.28651
11048.1947.5169611264.7950.1688411285.4452.5743911306.0847.5532811326.7350.42501
11553.8246.5096211718.9852.3582412173.1654.2340312235.0955.4625412255.4859.36812
#Mann= 3 , 0 , 0
8653.951  0.0448       08653.951  0.0448       012255.48  0.0448       0
#XS Ineff= 2 , 0
       09948.064        10035.22       0
Bank Sta=8653.951,12255.48
Exp/Cntr=0.3,0.1

Type RM Length L Ch R = 1 ,9179.738,595.607100,595.607100,595.607100
XS GIS Cut Line= 6
802876.818470895717550.278617844  802377.5936625717205.357883245
802070.301995844717028.274549916801528.635329127716955.357883245
801059.885329127717059.524549916  800408.8436625717533.482883245
#Sta/Elev= 30
9126.06353.315279208.67855.682369520.41650.027499628.33853.667279679.43852.13694
 9782.3143.550769974.20441.622159990.05939.71112 10001.636.0155610013.1435.70745
10024.6840.5254510034.2942.3342210074.3440.2108910204.1641.0238410426.1438.16027
10771.2639.2226110976.1442.0572111367.9843.6964611405.0942.54133 11442.2 46.1993
11466.9343.1911711514.6445.9654811528.7844.60218   1160345.6762811615.3644.11548
11633.5845.8179411689.5844.6243611887.4948.6270511899.86   50.5811919.8449.19051
#Mann= 3 , 0 , 0
9126.063   0.044       09126.063   0.044       011919.84   0.044       0
#XS Ineff= 2 , 0
       09907.423        10616.33       0
Bank Sta=9126.063,11919.84
Exp/Cntr=0.3,0.1

Type RM Length L Ch R = 1 ,8584.131,493.497400,493.497400,493.497400
XS GIS Cut Line= 6
803539.129657269717111.221897647 802675.53461948716675.668815285
802405.094352663 716565.12624386802244.834711373716484.926441133
  801986.9686625716382.441216573  801096.3436625716377.232883245
#Sta/Elev= 30
 8846.5175.706288950.611 66.5231 8972.7659.337558995.08859.168959006.25255.25981
9084.61756.007529141.00950.817779283.862 51.00169321.46155.512889344.01751.77588
 9389.1351.267819411.68760.699889434.24361.874969468.07849.847769490.63435.77222
9513.19141.486919748.11941.921359791.94136.455479923.51433.309679955.881  33.814
9977.24538.820979987.88337.037759998.522 31.376410019.8338.3966710285.3631.46627
10392.7934.7763910532.6832.8214810894.8136.6839311134.8234.2394811453.4838.68171
#Mann= 3 , 0 , 0
 8846.51   0.041       0 8846.51   0.041       011453.48   0.041       0
#XS Ineff= 2 , 0
       0                10672.47       0
Bank Sta=8846.51,11453.48
Exp/Cntr=0.3,0.1

Type RM Length L Ch R = 1 ,8090.633,493.497500,493.497500,493.497500
XS GIS Cut Line= 6
803672.816396117716672.490277082803106.751961946716373.306386724
802725.325152546716180.641392529802575.663578808716090.362842277
  802236.9686625716002.232883245801309.885329127715944.941216573
#Sta/Elev= 30
8844.52350.607098875.83349.03022  8909.649.347979044.94744.996399067.60542.33422
9101.59342.218179124.25143.972719183.30344.422229247.13741.23994 9310.97 41.1888
9353.52643.225669396.08243.38123 9417.3641.528299430.13732.268789438.63832.00189
9497.99331.71501 9520.4532.893149599.04831.661139889.90630.750689947.55132.42802
9970.90239.418059994.25430.13869   1000129.7310310041.0132.5194910064.3632.58094
10211.6129.6244810335.6129.5511810649.2731.6157511170.2733.0820511365.7536.06454
#Mann= 3 , 0 , 0
8844.523  0.0418       08844.523  0.0418       011365.75  0.0418       0
#XS Ineff= 2 , 0
       0 9717.06        10887.92       0
Bank Sta=8844.523,11365.75
Exp/Cntr=0.3,0.1

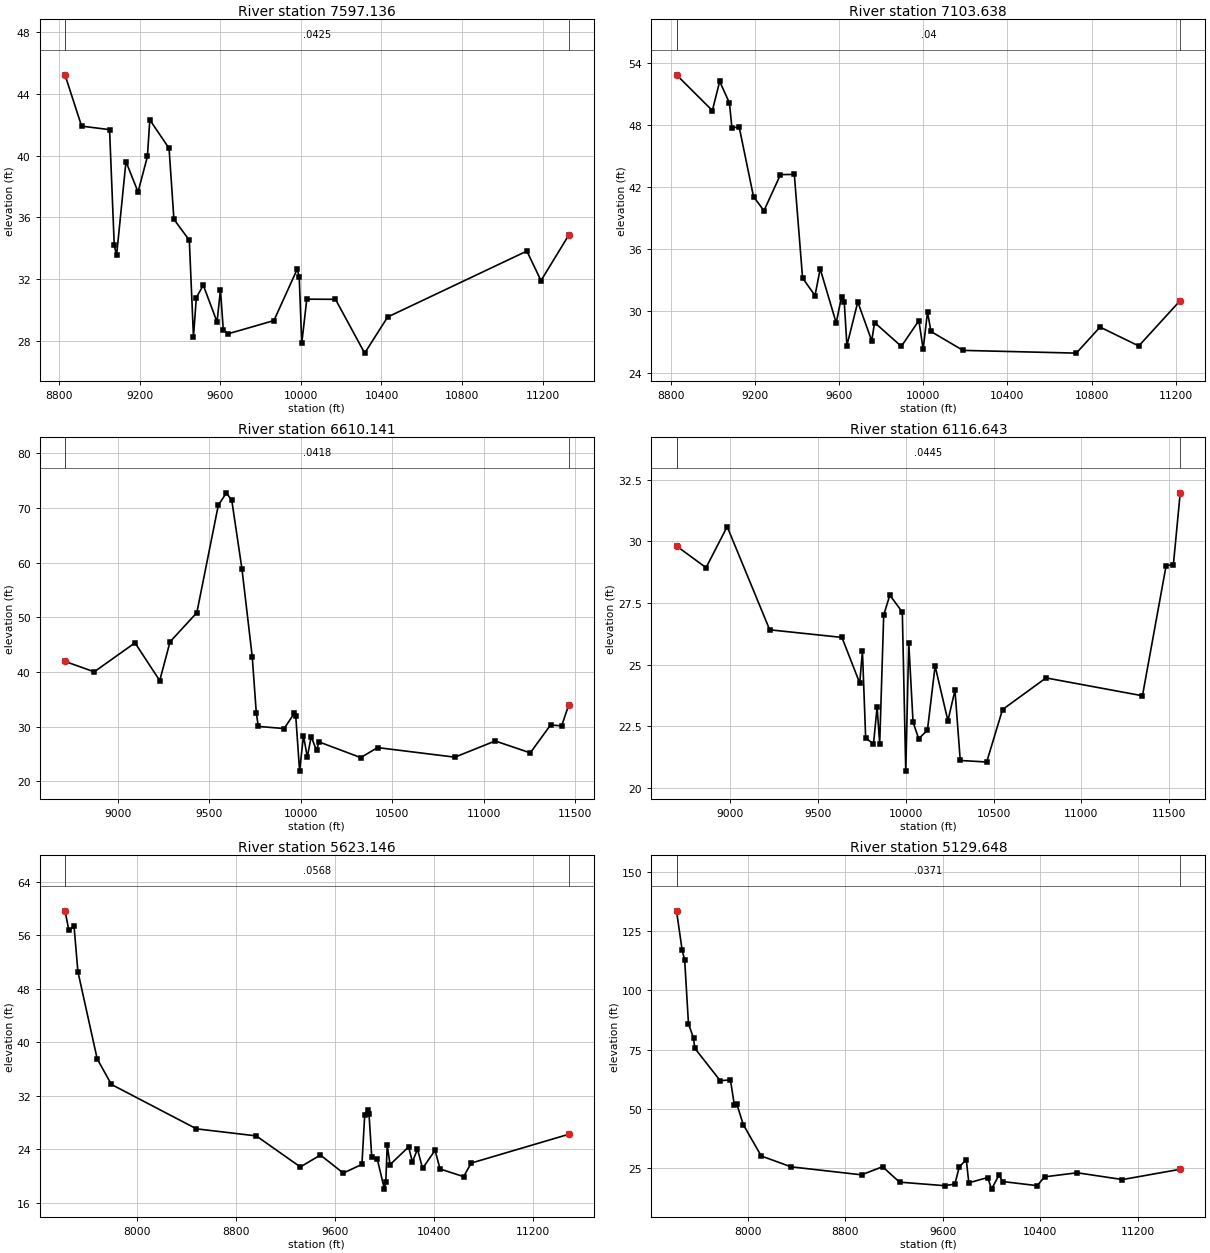
Type RM Length L Ch R = 1 ,7597.136,493.497400,493.497400,493.497400
XS GIS Cut Line= 6
803897.089966089716387.932471171803625.568161279716231.159104094
 803398.16255343716083.371455058802875.618802577 715694.11180301
 802533.84366253 715595.98288323  801627.5936625715559.524549901
#Sta/Elev= 30
8829.779 45.22518912.23541.903259050.94741.676569074.21134.188639085.84433.53631
9132.37239.609869192.19237.638039238.74339.939489250.58442.31209 9346.18 40.4649
9370.24635.86863 9446.6134.51497 9467.26 28.24769481.48630.804829516.08731.60165
9584.217 29.22129601.18331.306419615.11728.713099639.93228.459479866.28429.31213
9981.85632.638619991.82232.1462210004.3727.8311910029.4330.6990910171.7330.68867
10316.5827.2047910430.6729.5441211121.2333.8133411191.2931.89988 11328.834.83719
#Mann= 3 , 0 , 0
8829.779  0.0425       08829.779  0.0425       0 11328.8  0.0425       0
#XS Ineff= 2 , 0
       09518.532                       0
Bank Sta=8829.779,11328.8
Exp/Cntr=0.3,0.1

Type RM Length L Ch R = 1 ,7103.638,493.497500,493.497500,493.497500
XS GIS Cut Line= 6
804224.554897815716097.402794555803762.701610684715820.680287361
  803516.0712699715634.588825986803238.377805859 715365.37019138
803065.093662471715273.066216573802122.385329127 715064.73288323
#Sta/Elev= 30
8825.50352.868868996.09949.40587 9030.9352.235579077.37150.139579088.98147.75538
9123.81247.799769191.876 41.07429241.51639.705719320.14443.204739385.99743.22401
9425.34933.188189484.50631.490059509.13434.075729585.25428.841589610.78631.38022
9623.55230.876739636.31826.652369687.97430.873719754.47627.106389767.77628.88077
9895.12926.572499978.64129.06577    999926.29701 10019.829.9156110035.9728.01334
10188.79 26.180910727.8625.9156610840.5128.4403411024.8626.6100111222.1231.00787
#Mann= 3 , 0 , 0
8825.503    0.04       08825.503    0.04       011222.12    0.04       0
#XS Ineff= 2 , 0
       09683.826                       0
Bank Sta=8825.503,11222.12
Exp/Cntr=0.3,0.1

Type RM Length L Ch R = 1 ,6610.141,493.497500,493.497500,493.497500
XS GIS Cut Line= 6
804699.502615392715561.248659909803766.762456387715093.258704782
803231.760329127714882.441216573803070.301995844 714845.98288323
802544.260329127714819.941216573802106.760329127 714877.23288323
#Sta/Elev= 30
8712.56541.952718872.241 40.0433 9095.2345.342669230.42438.436689286.75445.53374
9433.21450.854419550.55470.499359594.72372.773149624.26571.380659680.07358.78131
 9735.88 42.8338 9758.1732.542079769.13930.063649910.31729.674519965.74432.44662
9973.75731.998179994.90321.8880710015.9728.3808410037.03 24.461310058.2228.20231
10087.2325.6816110101.0327.2267510328.7624.3652810421.0926.19083 10843.424.44031
11063.9527.4027611255.5825.2247111366.5230.3287711427.0330.1626411465.59 33.9862
#Mann= 3 , 0 , 0
8712.565  0.0418       08712.565  0.0418       011465.59  0.0418       0
#XS Ineff= 2 , 0
       09838.518                       0
Bank Sta=8712.565,11465.59
Exp/Cntr=0.3,0.1

Type RM Length L Ch R = 1 ,6116.643,493.497400,493.497400,493.497400
XS GIS Cut Line= 6
804919.291698992715137.668306455 804237.66831702714825.056316614
803629.142960548714483.486718908803539.051995844 714455.35788323
803195.301995844 714424.10788323802247.385329127714684.524549901
#Sta/Elev= 30
8692.24529.814218860.63728.93617 8981.1130.597669223.42126.417839635.16326.10953
9736.58424.259689752.08825.558059770.43222.032899815.02321.792359835.60923.28311
9850.419 21.8034  9873.327.014269908.20627.824239979.37327.13241    9999 20.6912
10016.1725.8771210040.4822.6776610072.79 22.004110122.5122.3494810166.1924.94854
10239.3522.7327510279.5123.9663310309.6421.1228610460.2521.0614310550.6323.18669
10798.54 24.468411348.1823.7449711482.99 29.014811524.4829.0624611563.4831.96858
#Mann= 3 , 0 , 0
8692.245  0.0445       08692.245  0.0445       011563.48  0.0445       0
#XS Ineff= 2 , 0
       0 9941.29                       0
Bank Sta=8692.245,11563.48
Exp/Cntr=0.3,0.1

Type RM Length L Ch R = 1 ,5623.146,493.497500,493.497500,493.497500
XS GIS Cut Line= 6
806405.883328375715054.488510869805507.281755463714771.098593134
803895.028086999714088.126949653803674.468662471714038.691216558
803221.343662471714085.566216558802605.477277564  714406.0170185
#Sta/Elev= 30
7419.478 59.6361 7451.4656.694557492.88357.29633 7523.9550.545427679.84337.48683
7794.58133.666288482.10527.023928965.24925.967989321.65521.325569483.90723.10442
9668.09220.407679819.23421.700189841.96829.163269865.44929.901199876.58429.19843
9898.85422.736199943.88622.4627910000.7818.0048710012.1719.0283710023.5624.61813
10046.3521.6660110196.4524.3218510227.1922.0521310268.19      2410309.1821.10538
10410.31 23.819510450.5221.0200910641.5319.8725810701.8521.8983511490.2626.20652
#Mann= 3 , 0 , 0
7419.478  0.0568       07419.478  0.0568       011490.26  0.0568       0
#XS Ineff= 2 , 0
       0 9868.89         10787.5       0
Bank Sta=7419.478,11490.26
Exp/Cntr=0.3,0.1

Type RM Length L Ch R = 1 ,5129.648,493.497400,493.497400,493.497400
XS GIS Cut Line= 6
806549.412700713714497.332256764804569.888594002713798.601662397
803846.343662471713616.816216558803585.926995784 713611.60788323
803247.385329127713715.774549916802669.260329127714054.316216558
#Sta/Elev= 30
7415.687133.61577461.839117.03127482.622112.85967513.79685.962327555.36379.84787
7565.75475.584067774.27761.91483 7858.05 62.22747889.47351.844727910.543 52.0388
7963.21943.368318110.914 30.11648355.27525.53591 8933.8322.160949105.63325.58408
9245.11319.08194 9615.5817.572069698.99218.267599735.38925.482099792.51928.60991
9813.265 18.79769968.85621.017149999.79416.1256410060.8422.0587810091.36 19.3297
10374.3117.5849710434.3221.3056910702.2523.0317311073.9820.1653911547.5724.51211
#Mann= 3 , 0 , 0
7415.687  0.0371       07415.687  0.0371       011547.57  0.0371       0
#XS Ineff= 2 , 0
       09762.211                       0
Bank Sta=7415.687,11547.57
Exp/Cntr=0.3,0.1

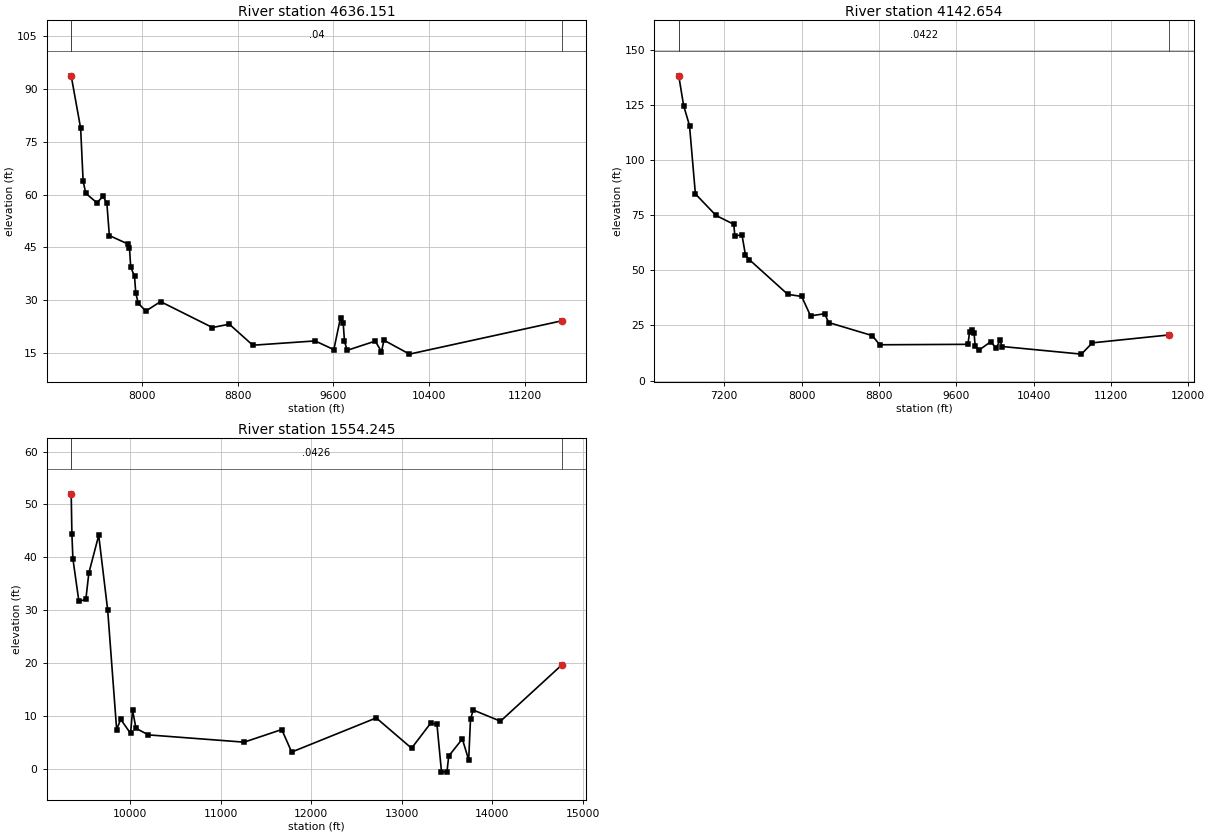
Type RM Length L Ch R = 1 ,4636.151,493.497500,493.497500,493.497500
XS GIS Cut Line= 6
806610.915006795714127.928889587805638.471882002713807.793723199
804402.554002622713246.320006121804107.891281209 713158.48288323
803585.926995784 713158.48288323802763.792277298713478.201940419
#Sta/Elev= 30
7411.92793.721347490.77478.832767511.546 63.77967533.81160.369497625.93557.68027
  7678.259.49972 7709.5657.579347730.46648.366497887.79345.933177898.31244.86018
7908.83139.359897940.38736.857527950.90632.021197971.94329.096368035.36426.94489
8157.65329.613898590.84722.254158731.58123.209578927.746 17.22869447.96218.44981
9604.123 15.97819659.89425.083199681.96823.585349692.92118.386079714.82915.78015
9949.97618.3984310001.6915.3904910022.3418.6553810234.8614.7019411506.0524.15315
#Mann= 3 , 0 , 0
7411.927    0.04       07411.927    0.04       011506.05    0.04       0
#XS Ineff= 2 , 0
       09652.175        10542.87       0
Bank Sta=7411.927,11506.05
Exp/Cntr=0.3,0.1

Type RM Length L Ch R = 1 ,4142.654,2588.408700,2588.408700,2588.408700
XS GIS Cut Line= 6
807532.718807131714011.550012887805803.152545393713409.472169191
804757.394026309712992.134324998804025.774362713712613.980568409
803554.676995784712663.691216558802893.218662471 713127.23288323
#Sta/Elev= 30
6730.422138.20146780.946124.68026841.659115.64596902.52784.650777115.56674.87107
7299.75270.85893 7310.3465.636187384.45566.045637419.90756.97103 7458.5754.88692
7857.988 39.07058001.34538.14922 8093.1929.326678238.57430.287648281.15526.29817
8732.47820.363388807.84616.212459721.10916.416659737.78521.839629761.19823.09187
9784.61221.482049796.31915.50855 9831.4413.647459956.169 17.575910012.7414.76369
10053.3518.1605810074.6915.43056 10894.911.97151 11007.617.0854811803.4920.68682
#Mann= 3 , 0 , 0
6730.422  0.0422       06730.422  0.0422       011803.49  0.0422       0
#XS Ineff= 2 , 0
       09760.379        11035.07       0
Bank Sta=6730.422,11803.49
Exp/Cntr=0.3,0.1

Type RM Length L Ch R = 1 ,1554.245,120.227400,120.227400,120.227400
XS GIS Cut Line= 6
805722.213720292 710349.50268133804010.871127695711080.492264688
803211.391961068711304.450598001802578.304754943711414.672522187
800817.835738361711450.332265362800499.576227646711429.761701257
#Sta/Elev= 30
9351.14252.009259359.06344.322039370.04439.724979435.928 31.67619512.79332.01398
9545.73536.993179654.94444.159339754.36829.945879853.1947.3571779897.1179.350868
10006.926.66541910028.8811.0380810066.487.62984610204.586.38933411260.275.015534
11675.67  7.399411785.423.14379912718.919.60237613109.133.86748213319.138.594061
13389.13 8.4265613439.16 -0.559113499.23-0.6561713519.262.38527613669.445.626916
13739.551.65179113759.719.40899313789.9511.0975314090.628.97991714766.7619.61438
#Mann= 3 , 0 , 0
9351.142  0.0426       09351.142  0.0426       014766.76  0.0426       0
#XS Ineff= 2 , 0
       0                12245.52       0
Bank Sta=9351.142,14766.76
Exp/Cntr=0.3,0.1