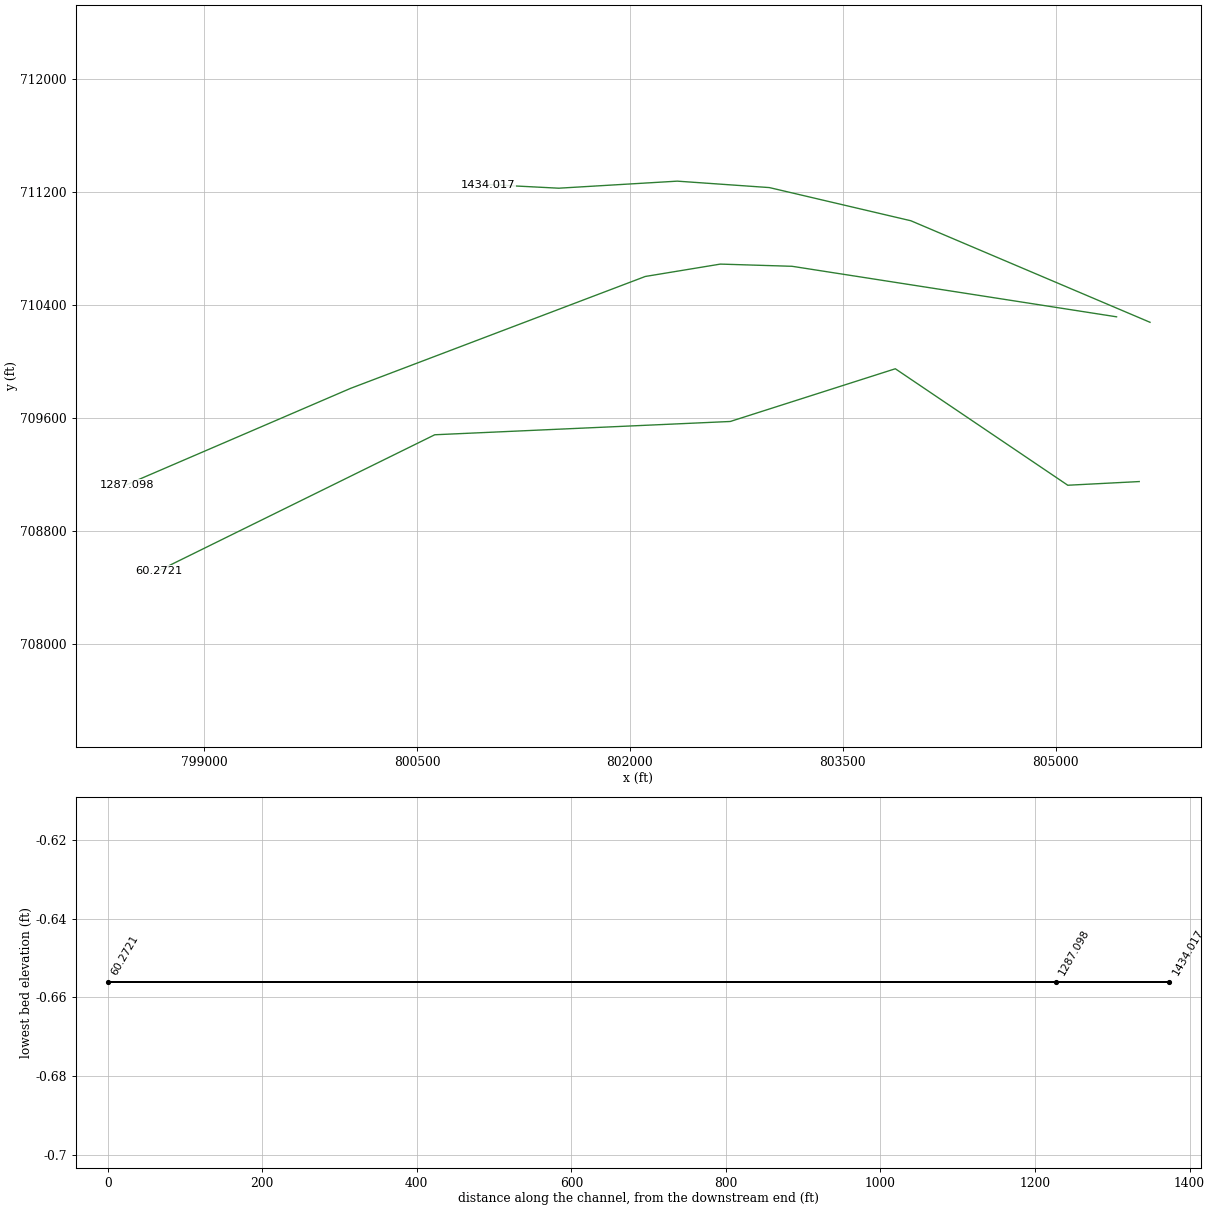
HEC-RAS study 6888_ras.prj: 6888

--- 6888_ras.g01 (geometry) --- (continued)

Type RM Length L Ch R = 3 ,1483.194,,,
BEGIN DESCRIPTION:
END DESCRIPTION:
Bridge Culvert--1,0,-1,-1, 0
Deck Dist Width WeirC Skew NumUp NumDn MinLoCord MaxHiCord MaxSubmerge Is_Ogee
38.113700,44.000000,2.6,0, 52, 52, , , 0.95, 0, 0,0,,
 9457.09 9461.88 9472.74 9482.15 9483.60 9494.46 9505.32 9527.04 9537.90 9548.76
 9559.62 9570.48 9581.34 9584.71 9592.20 9603.06 9610.35 9613.92 9617.66 9759.29
 9759.2913639.2913639.2913830.6513840.6513860.6613880.6713910.6813950.6813980.69
14070.7014130.7114150.7114170.7114180.7214200.7214210.7214230.7214240.7214250.73
14260.7314310.7314320.7414340.7414350.7414360.7414390.7514400.7514420.7514480.76
14580.7714644.14
   43.03   40.85   33.62   30.66   30.46   30.70   31.06   31.31   30.93   30.93
   32.06   35.56   40.81   42.35   45.62   49.97   50.99   51.15   51.00   50.34
   50.34   32.32   32.32   31.43   31.49   31.83   32.06   32.27   32.71   32.90
   33.34   33.51   33.68   33.59   33.70   33.75   33.87   33.87   33.79   33.88
   33.82   33.89   33.71   33.79   33.68   33.72   33.56   33.40   33.43   32.98
   32.07   31.10
 -956.97 -959.15 -966.38 -969.34 -969.54 -969.30 -968.94 -968.69 -969.07 -969.07
 -967.94 -964.44 -959.19 -957.65 -954.38 -950.03 -949.01 -948.85 -949.00 -949.66
   42.84   24.82 -967.68 -968.57 -968.51 -968.17 -967.94 -967.73 -967.29 -967.10
 -966.66 -966.49 -966.32 -966.41 -966.30 -966.25 -966.13 -966.13 -966.21 -966.12
 -966.18 -966.11 -966.29 -966.21 -966.32 -966.28 -966.44 -966.60 -966.57 -967.02
 -967.93 -968.90
 9457.09 9461.88 9472.74 9482.15 9483.60 9494.46 9505.32 9527.04 9537.90 9548.76
 9559.62 9570.48 9581.34 9584.71 9592.20 9603.06 9610.35 9613.92 9617.66 9794.46
 9794.4613674.4613674.4613830.6513840.6513860.6613880.6713910.6813950.6813980.69
14070.7014130.7114150.7114170.7114180.7214200.7214210.7214230.7214240.7214250.73
14260.7314310.7314320.7414340.7414350.7414360.7414390.7514400.7514420.7514480.76
14580.7714644.14
   43.03   40.85   33.62   30.66   30.46   30.70   31.06   31.31   30.93   30.93
   32.06   35.56   40.81   42.35   45.62   49.97   50.99   51.15   51.00   50.18
   50.18   32.15   32.15   31.43   31.49   31.83   32.06   32.27   32.71   32.90
   33.34   33.51   33.68   33.59   33.70   33.75   33.87   33.87   33.79   33.88
   33.82   33.89   33.71   33.79   33.68   33.72   33.56   33.40   33.43   32.98
   32.07   31.10
 -956.97 -959.15 -966.38 -969.34 -969.54 -969.30 -968.94 -968.69 -969.07 -969.07
 -967.94 -964.44 -959.19 -957.65 -954.38 -950.03 -949.01 -948.85 -949.00 -949.82
   42.68   24.65 -967.85 -968.57 -968.51 -968.17 -967.94 -967.73 -967.29 -967.10
 -966.66 -966.49 -966.32 -966.41 -966.30 -966.25 -966.13 -966.13 -966.21 -966.12
 -966.18 -966.11 -966.29 -966.21 -966.32 -966.28 -966.44 -966.60 -966.57 -967.02
 -967.93 -968.90
Pier Skew, UpSta & Num, DnSta & Num=  ,9882.58, 2 ,9917.75, 2 , 0 , 0 , 0 ,,
    4.00    4.00
 -950.23   49.77
    4.00    4.00
 -950.39   49.61
Pier Skew, UpSta & Num, DnSta & Num=  ,10007.87, 2 ,10043.04, 2 , 0 , 0 , 0 ,,
    4.00    4.00
 -950.81   49.19
    4.00    4.00
 -950.97   49.03
Pier Skew, UpSta & Num, DnSta & Num=  ,10133.16, 2 ,10168.33, 2 , 0 , 0 , 0 ,,
    4.00    4.00
 -951.39   48.61
    4.00    4.00
 -951.56   48.44
Pier Skew, UpSta & Num, DnSta & Num=  ,10258.45, 2 ,10293.62, 2 , 0 , 0 , 0 ,,
    4.00    4.00
 -951.97   48.03
    4.00    4.00
 -952.14   47.86
Pier Skew, UpSta & Num, DnSta & Num=  ,10383.74, 2 ,10418.91, 2 , 0 , 0 , 0 ,,
    4.00    4.00
 -952.56   47.44
    4.00    4.00
 -952.72   47.28
Pier Skew, UpSta & Num, DnSta & Num=  ,10509.03, 2 ,10544.20, 2 , 0 , 0 , 0 ,,
    4.00    4.00
 -953.14   46.86
    4.00    4.00
 -953.30   46.70
Pier Skew, UpSta & Num, DnSta & Num=  ,10634.32, 2 ,10669.49, 2 , 0 , 0 , 0 ,,
    4.00    4.00
 -953.72   46.28
    4.00    4.00
 -953.88   46.12
Pier Skew, UpSta & Num, DnSta & Num=  ,10759.61, 2 ,10794.78, 2 , 0 , 0 , 0 ,,
    4.00    4.00
 -954.30   45.70
    4.00    4.00
 -954.47   45.53
Pier Skew, UpSta & Num, DnSta & Num=  ,10884.90, 2 ,10920.07, 2 , 0 , 0 , 0 ,,
    4.00    4.00
 -954.89   45.11
    4.00    4.00
 -955.05   44.95
Pier Skew, UpSta & Num, DnSta & Num=  ,11010.19, 2 ,11045.36, 2 , 0 , 0 , 0 ,,
    4.00    4.00
 -955.47   44.53
    4.00    4.00
 -955.63   44.37
Pier Skew, UpSta & Num, DnSta & Num=  ,11135.48, 2 ,11170.65, 2 , 0 , 0 , 0 ,,
    4.00    4.00
 -956.05   43.95
    4.00    4.00
 -956.21   43.79
Pier Skew, UpSta & Num, DnSta & Num=  ,11260.77, 2 ,11295.95, 2 , 0 , 0 , 0 ,,
    4.00    4.00
 -956.63   43.37
    4.00    4.00
 -956.80   43.20
Pier Skew, UpSta & Num, DnSta & Num=  ,11386.06, 2 ,11421.24, 2 , 0 , 0 , 0 ,,
    4.00    4.00
 -957.21   42.79
    4.00    4.00
 -957.38   42.62
Pier Skew, UpSta & Num, DnSta & Num=  ,11511.35, 2 ,11546.53, 2 , 0 , 0 , 0 ,,
    4.00    4.00
 -957.80   42.20
    4.00    4.00
 -957.96   42.04
Pier Skew, UpSta & Num, DnSta & Num=  ,11636.64, 2 ,11671.82, 2 , 0 , 0 , 0 ,,
    4.00    4.00
 -958.38   41.62
    4.00    4.00
 -958.54   41.46
Pier Skew, UpSta & Num, DnSta & Num=  ,11761.93, 2 ,11797.11, 2 , 0 , 0 , 0 ,,
    4.00    4.00
 -958.96   41.04
    4.00    4.00
 -959.12   40.88
Pier Skew, UpSta & Num, DnSta & Num=  ,11887.22, 2 ,11922.40, 2 , 0 , 0 , 0 ,,
    4.00    4.00
 -959.54   40.46
    4.00    4.00
 -959.71   40.29
Pier Skew, UpSta & Num, DnSta & Num=  ,12012.51, 2 ,12047.69, 2 , 0 , 0 , 0 ,,
    4.00    4.00
 -960.13   39.87
    4.00    4.00
 -960.29   39.71
Pier Skew, UpSta & Num, DnSta & Num=  ,12137.81, 2 ,12172.98, 2 , 0 , 0 , 0 ,,
    4.00    4.00
 -960.71   39.29
    4.00    4.00
 -960.87   39.13
Pier Skew, UpSta & Num, DnSta & Num=  ,12263.10, 2 ,12298.27, 2 , 0 , 0 , 0 ,,
    4.00    4.00
 -961.29   38.71
    4.00    4.00
 -961.45   38.55
Pier Skew, UpSta & Num, DnSta & Num=  ,12388.39, 2 ,12423.56, 2 , 0 , 0 , 0 ,,
    4.00    4.00
 -961.87   38.13
    4.00    4.00
 -962.04   37.96
Pier Skew, UpSta & Num, DnSta & Num=  ,12513.68, 2 ,12548.85, 2 , 0 , 0 , 0 ,,
    4.00    4.00
 -962.45   37.55
    4.00    4.00
 -962.62   37.38
Pier Skew, UpSta & Num, DnSta & Num=  ,12638.97, 2 ,12674.14, 2 , 0 , 0 , 0 ,,
    4.00    4.00
 -963.04   36.96
    4.00    4.00
 -963.20   36.80
Pier Skew, UpSta & Num, DnSta & Num=  ,12764.26, 2 ,12799.43, 2 , 0 , 0 , 0 ,,
    4.00    4.00
 -963.62   36.38
    4.00    4.00
 -963.78   36.22
Pier Skew, UpSta & Num, DnSta & Num=  ,12889.55, 2 ,12924.72, 2 , 0 , 0 , 0 ,,
    4.00    4.00
 -964.20   35.80
    4.00    4.00
 -964.36   35.64
Pier Skew, UpSta & Num, DnSta & Num=  ,13014.84, 2 ,13050.01, 2 , 0 , 0 , 0 ,,
    4.00    4.00
 -964.78   35.22
    4.00    4.00
 -964.95   35.05
Pier Skew, UpSta & Num, DnSta & Num=  ,13140.13, 2 ,13175.30, 2 , 0 , 0 , 0 ,,
    4.00    4.00
 -965.36   34.64
    4.00    4.00
 -965.53   34.47
Pier Skew, UpSta & Num, DnSta & Num=  ,13265.42, 2 ,13300.59, 2 , 0 , 0 , 0 ,,
    4.00    4.00
 -965.95   34.05
    4.00    4.00
 -966.11   33.89
Pier Skew, UpSta & Num, DnSta & Num=  ,13390.71, 2 ,13425.88, 2 , 0 , 0 , 0 ,,
    4.00    4.00
 -966.53   33.47
    4.00    4.00
 -966.69   33.31
Pier Skew, UpSta & Num, DnSta & Num=  ,13516.00, 2 ,13551.17, 2 , 0 , 0 , 0 ,,
    4.00    4.00
 -967.11   32.89
    4.00    4.00
 -967.27   32.73
BR Coef=-1 , 0 , 0 ,, 0 ,,,0.8,0,1,0,
WSPro=,,,, 1 ,,,, 0 ,,,, 0 ,,,,-1 ,-1 ,-1 , 0 , 0 , 0 , 0 , 0
BC Design=,, 0 ,, 0 ,,,,,,

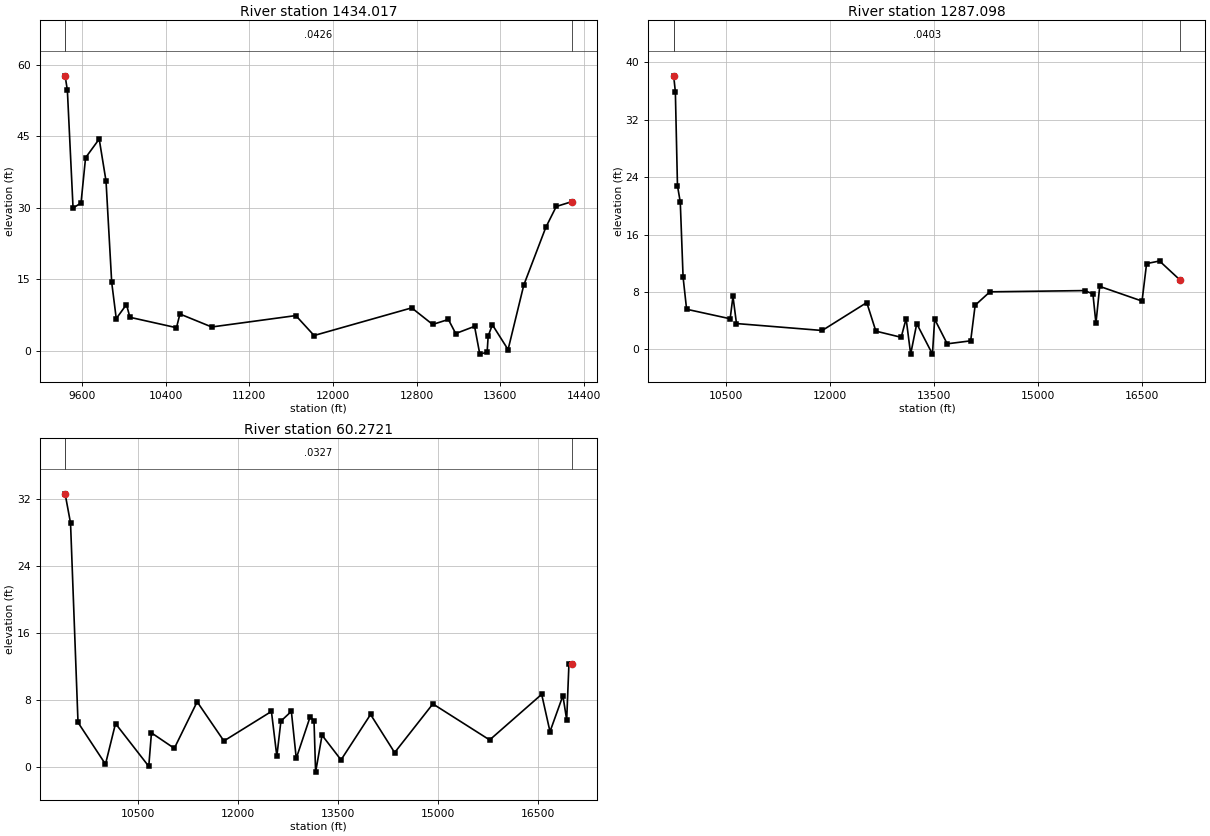
Type RM Length L Ch R = 1 ,1434.017,146.919600,146.919600,146.919600
XS GIS Cut Line= 6
805664.922053635710278.322125793803979.621127695 710997.15893133
802982.592682838711232.016293123802333.721155047711277.589209795
801498.217682838711227.676015347800999.125707615711253.447663711
#Sta/Elev= 30
9438.347 57.70149460.00654.655969514.364  29.9799590.46631.035529633.95240.52191
9764.41244.449849829.64235.641199884.00114.390079927.487  6.799110025.339.749683
10057.95 7.0679810503.694.884775 10536.37.75938910840.715.03715711645.157.427351
 11819.83.24650912753.599.04308612954.075.56720113104.376.61090613174.513.659885
13354.865.16611113404.96-0.65617 13475.1 -0.255513485.123.134619 13525.25.502246
13675.490.28997313825.7313.8255814036.2525.9153214136.4330.3045614282.4631.29273
#Mann= 3 , 0 , 0
9438.347  0.0426       09438.347  0.0426       014282.46  0.0426       0
#XS Ineff= 2 , 0
       0                12308.93       0
Bank Sta=9438.347,14282.46
Exp/Cntr=0.3,0.1

Type RM Length L Ch R = 1 ,1287.098,1226.825700,1226.825700,1226.825700
XS GIS Cut Line= 6
805429.042424023710317.124209136 803142.58409068710674.763098001
802637.375757366710690.388098001802108.038123555710602.805144518
800030.926040107709810.557271467 798455.09907439709129.447497926
#Sta/Elev= 30
9749.943 38.10889774.27835.867159804.64322.802429845.12920.516379885.61510.05797
9936.2235.59491110563.764.26951510604.257.38080510654.863.60282511889.692.636022
12532.016.52442712663.282.54557713028.181.68589313099.134.29313113164.53-0.65617
13252.353.58061313478.59-0.6561713510.534.21371613691.06 0.7793714029.341.195454
 14093.7 6.1521314306.448.02240715671.598.19523715790.777.72775515834.253.638989
 15888.68.78005916498.446.73319316564.0611.9541916750.3212.3168717046.789.658008
#Mann= 3 , 0 , 0
9749.943  0.0403       09749.943  0.0403       017046.78  0.0403       0
#XS Ineff= 2 , 0
       0                12460.52       0
Bank Sta=9749.943,17046.78
Exp/Cntr=0.3,0.1

Type RM Length L Ch R = 1 , 60.2721,0.000000,0.000000,0.000000
XS GIS Cut Line= 6
805588.755374163709150.764336661805085.283151954709124.722669989
803870.005374193709949.375447795802706.810929745709576.111558869
800624.396791607 709482.08139731798681.051884234 708520.68093434
#Sta/Elev= 30
9401.27332.621189482.74729.123159594.9695.28364610007.680.29115210158.185.152515
10657.690.03439210697.974.03897611041.292.18803811384.227.751985   117863.069901
12500.016.59976512581.321.23431712642.315.44351112799.336.610806 12872.9  0.9911
13080.875.95035413139.445.51413413163.52-0.6561713260.323.75798613545.270.806384
13988.91 6.2378114350.321.67987414924.797.50263415777.38 3.1925116558.738.646535
16683.984.18520316877.558.48101616934.485.59745216968.6412.32347 17007.312.31464
#Mann= 3 , 0 , 0
9401.273  0.0327       09401.273  0.0327       0 17007.3  0.0327       0
#XS Ineff= 2 , 0
       0                13048.05       0
Bank Sta=9401.273,17007.3
Exp/Cntr=0.3,0.1